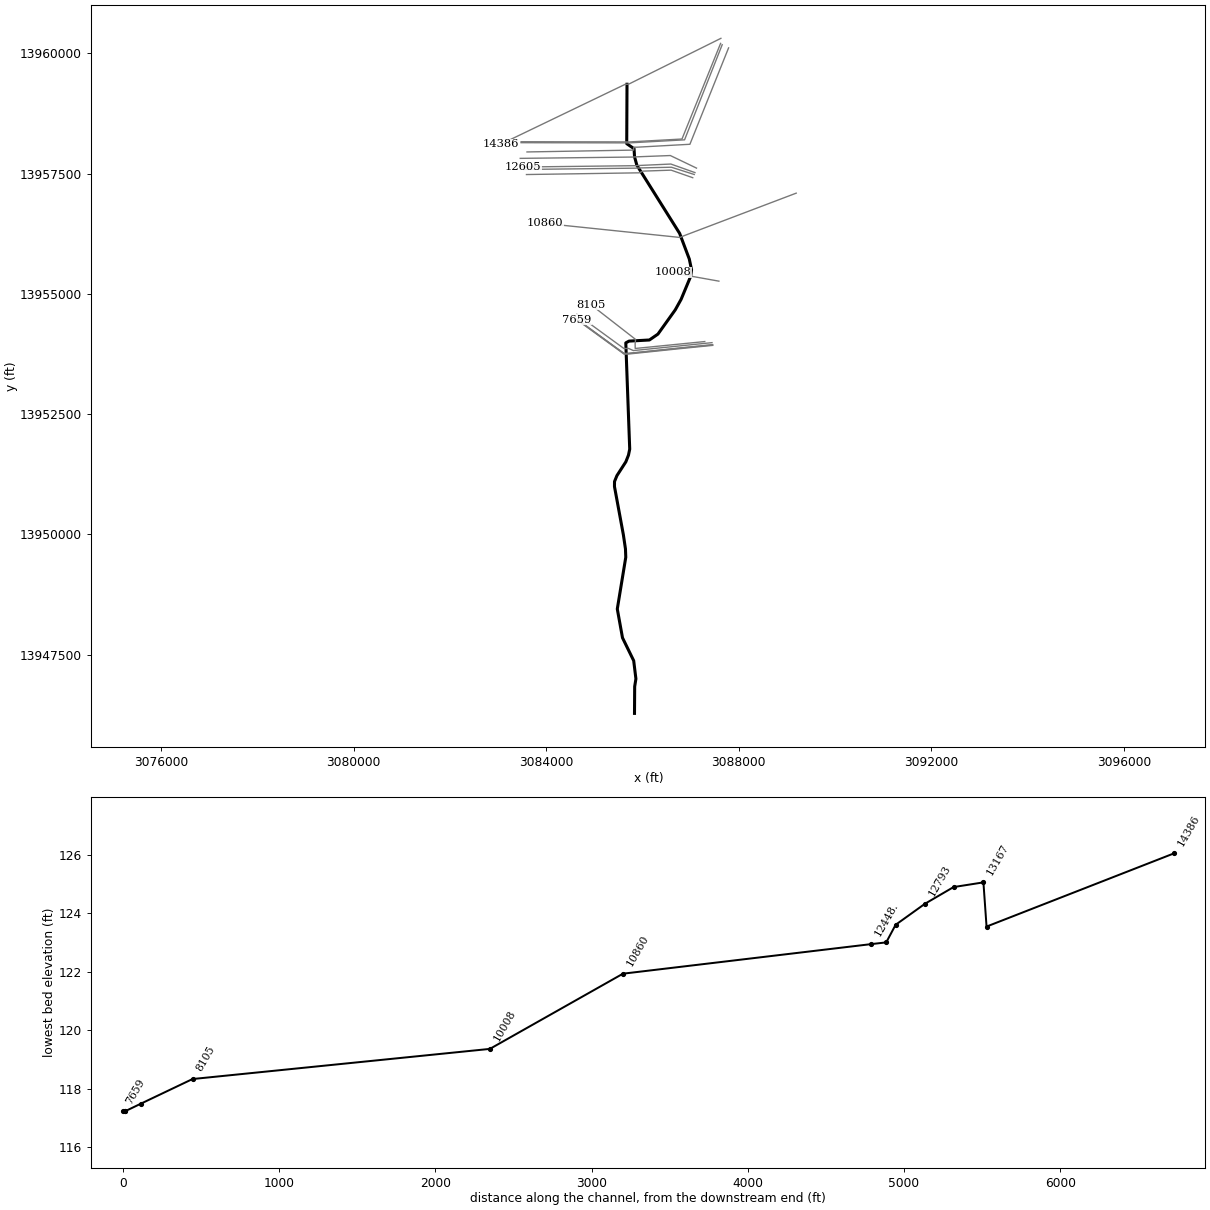
--- K124-02-00.prj (project) ---

Proj Title=K124-02-00
Current Plan=p02
Default Exp/Contr=.3,.1
English Units
Geom File=g01
Flow File=f01
Flow File=f02
Plan File=p01
Plan File=p02
Y Axis Title=Elevation
X Axis Title(PF)=Main Channel Distance
X Axis Title(XS)=Station
BEGIN DESCRIPTION:
Cypress Bayou Watershed
Kothman Gully
HCFCD Unit K124-02-00
Flood Hazard Model
10, 2, 1, 0.2%
Filename K124-02-00
Prepared by:  Halff Associates Inc  DATE:  June 30, 2004
Reviewed by:  _____________________  DATE:  __________________
STATUS (Final)
END DESCRIPTION:
DSS File=dss
DSS Export Rating Curves= 0
DSS Export Rating Curve Sorted= 0
DSS Export Volume Flow Curves= 0
DXF OffsetX= 0
DXF OffsetY= 0
DXF ScaleX= 1
DXF ScaleY= 10

--- K124-02-00.p02 (plan) ---

Plan Title=Floodway
Version=Version 3.0.1  May 2012
Short Identifier=Eff+LOMR FW
Geom File=g01
Flow File=f02
Subcritical Flow
K Sum by GR= 0
Std Step Tol= 0.01
Critical Tol= 0.01
Num of Std Step Trials= 20
Max Error Tol= 0.3
Flow Tol Ratio= 0.001
Split Flow NTrial= 30
Split Flow Tol= 0.02
Split Flow Ratio= 0.02
Log Output Level= 0
Friction Slope Method= 1
Unsteady Friction Slope Method= 2
Parabolic Critical Depth
Global Vel Dist= 0 , 0 , 0
Global Log Level= 0
CheckData=True
Encroach Param=-1 ,0,0, 2
Encroach River=K124-02-00
Encroach Reach=Reach - 1
Encroach Node=14386
       1  4972.9  5055.5
Encroach Node=14356
       1  4972.9  5055.5
Encroach Node=13187
       1  4757.5  5055.5
Encroach Node=13167
       1  4757.5 5023.25
Encroach Node=13157
       1  4757.5 5023.25
Encroach Node=12976
       1    4920 5023.25
Encroach Node=12793
       1  4932.6  5027.5
Encroach Node=12605
       1  4932.6  5020.5
Encroach Node=12595
       1  4972.9  5039.5
Encroach Node=12545
       1  4932.6  5020.5
Encroach Node=12448.
       1  4957.2 5021.59
Encroach Node=10860
       1  4972.9  5039.5
Encroach Node=10008
       1  4970.2  5057.3
Encroach Node=8105
       1  4966.6  5057.6
Encroach Node=7775.
       1 4958.48 5047.49
Encroach Node=7674
       1    4956  5044.4
Encroach Node=7673
       1    4956  5044.4
Encroach Node=7670
       1    4956  5044.4
Encroach Node=7659
       1    4956  5044.4
Encroach Node=7649
       1    4956  5044.4
Encroach Node=7560
       1    4956  5044.4
Encroach Node=7463.
       1  4945.7 5058.79
Encroach Node=6665
       1 4930.13 5058.79
Encroach Node=6571
       1 4915.48  5060.3
Encroach Node=6561
       1 4915.48  5060.3
Encroach Node=6520
       1 4915.48  5060.3
Encroach Node=6415.
       1  4924.1    5044
Encroach Node=5672
       1  4974.3  5042.1
Encroach Node=4830.
       1  4954.9  5052.1
Encroach Node=4726
       1  4954.9  5052.1
Encroach Node=4716
       1  4954.9  5052.1
Encroach Node=4665
       1  4964.9  5036.7
Encroach Node=4565.00
       1 4963.93  5036.1
Encroach Node=3195
       1  4950.6  5027.9
Encroach Node=2218.
       1    4971 5027.54
Encroach Node=2118
       1  4973.3  5027.5
Encroach Node=2108
       1  4973.3  5027.5
Encroach Node=2081
       1  4973.3  5027.5
Encroach Node=1987.
       1 4972.52 5028.04
Encroach Node=749
       1 4962.23 5035.13
Encroach Node=649
       1  4961.4  5035.7
Encroach Node=640
       1  4961.4  5035.7
Encroach Node=628
       1  4961.4  5035.7
Encroach Node=572
       1  4946.4  5053.3
Encroach Node=562
       1  4946.4  5053.3
Encroach Node=474
       1  4946.4  5053.3
Encroach Node=370
       1  4948.9    5038
Encroach Reach=K124-02-00_0004
Encroach Node=14386
       1  4972.9  5055.5
Encroach Node=13187
       1  4757.5  5055.5
Encroach Node=13167
       1  4757.5 5023.25
Encroach Node=13157
       1  4757.5 5023.25
Encroach Node=12976
       1    4920 5023.25
Encroach Node=12793
       1  4932.6  5027.5
Encroach Node=12605
       1  4932.6  5020.5
Encroach Node=12595
       1  4972.9  5039.5
Encroach Node=12545
       1  4932.6  5020.5
Encroach Node=12448.
       1  4957.2 5021.59
Encroach Node=10860
       1  4972.9  5039.5
Encroach Node=10008
       1  4970.2  5057.3
Encroach Node=8105
       1  4966.6  5057.6
Encroach Node=7775.
       1 4958.48 5047.49
Encroach Node=7674
       1    4956  5044.4
Encroach Node=7673
       1    4956  5044.4
Encroach Node=7670
       1    4956  5044.4
Encroach Node=7659
       1    4956  5044.4
Encroach Node=7649
       1    4956  5044.4
Encroach Node=7560
       1    4956  5044.4
Encroach Node=7463.
       1  4945.7 5058.79
Encroach Node=6665
       1 4930.13 5058.79
Encroach Node=6571
       1 4915.48  5060.3
Encroach Node=6561
       1 4915.48  5060.3
Encroach Node=6520
       1 4915.48  5060.3
Encroach Node=6415.
       1  4924.1    5044
Encroach Node=5672
       1  4974.3  5042.1
Encroach Node=4830.
       1  4954.9  5052.1
Encroach Node=4726
       1  4954.9  5052.1
Encroach Node=4716
       1  4954.9  5052.1
Encroach Node=4665
       1  4964.9  5036.7
Encroach Node=4565.00
       1 4963.93  5036.1
Encroach Node=3195
       1  4950.6  5027.9
Encroach Node=2218.
       1    4971 5027.54
Encroach Node=2118
       1  4973.3  5027.5
Encroach Node=2108
       1  4973.3  5027.5
Encroach Node=2081
       1  4973.3  5027.5
Encroach Node=1987.
       1 4972.52 5028.04
Encroach Node=749
       1 4962.23 5035.13
Encroach Node=649
       1  4961.4  5035.7
Encroach Node=640
       1  4961.4  5035.7
Encroach Node=628
       1  4961.4  5035.7
Encroach Node=572
       1  4946.4  5053.3
Encroach Node=562
       1  4946.4  5053.3
Encroach Node=474
       1  4946.4  5053.3
Encroach Node=370
       1  4948.9    5038
BEGIN DESCRIPTION:
FEMA Effective June 2007 + LOMR 16-06-1540P
END DESCRIPTION:
Computation Interval=1HOUR
Output Interval=1HOUR
Run HTab= 0
Run UNet= 0
Run PostProcess= 0
UNET Theta= 1
UNET ZTol= 0.02
UNET ZSATol= 0.1
UNET MxIter= 20
UNET MaxInSteps= 20
UNET DtIC= 0
UNET DtMin= 0
UNET MaxCRTS= 20
UNET WFStab= 2
UNET SFStab= 1
UNET WFX= 1
UNET SFX= 1
UNET Convert EG Bridges=-1
UNET Use Existing IB Tables=-1
Instantaneous Interval=1HOUR
DSS File=dss
Write IC File= 0
IC Time=0
Write Velocity= 0
Write Detailed= 0

--- K124-02-00.p01 (plan) ---

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Plan Title=FEMA Effective 2016
Short Identifier=Eff+LOMR MP
Geom File=g01
Flow File=f01
Encroach Param=-1 ,0,0, 0

--- K124-02-00.f02 (steady flow) ---

Flow Title=Floodway
Version=Version 3.0.1  Mar 2001
Number of Profiles= 2
Profile Names=1PCT_100yr, 1PCTFloodway_100yrFW
River Rch & RM=K124-02-00,K124-02-00_0004,14386
     440     440
River Rch & RM=K124-02-00,K124-02-00_0004,13167
     470     470
River Rch & RM=K124-02-00,K124-02-00_0004,12605
     600     600
River Rch & RM=K124-02-00,K124-02-00_0004,10860
     680     680
River Rch & RM=K124-02-00,K124-02-00_0004,10008
     890     890
River Rch & RM=K124-02-00,K124-02-00_0004,8105
     950     950
River Rch & RM=K124-02-00,K124-02-00_0004,7659
    1070    1070
River Rch & RM=K124-02-00,K124-02-00_0004,6571
    1170    1170
River Rch & RM=K124-02-00,K124-02-00_0004,5672
    1300    1300
River Rch & RM=K124-02-00,K124-02-00_0004,4726
    1390    1390
River Rch & RM=K124-02-00,K124-02-00_0004,3195
    1460    1460
River Rch & RM=K124-02-00,K124-02-00_0004,2118
    1577    1577
Boundary for River Rch & Prof#=K124-02-00,K124-02-00_0004, 1
Up Type= 0
Dn Type= 3
Dn Slope=.0064
Boundary for River Rch & Prof#=K124-02-00,K124-02-00_0004, 2
Up Type= 0
Dn Type= 3
Dn Slope=.0064
DSS Import GetInterval= 0
DSS Import GetPeak= 0
DSS Import FillOption= 0

--- K124-02-00.f01 (steady flow) ---

Flow Title=FEMA Effective May 2016
Version=Version 3.0.1  May 2012
Number of Profiles= 4
Profile Names=10PCT_10yr, 2PCT_50yr, 1PCT_100yr, 0.2PCT_500yr
River Rch & RM=K124-02-00,K124-02-00_0004 ,14386
     230     370     440     650
River Rch & RM=K124-02-00,K124-02-00_0004 ,13167
     250     390     470     700
River Rch & RM=K124-02-00,K124-02-00_0004 ,12605
     320     500     600     900
River Rch & RM=K124-02-00,K124-02-00_0004 ,10860
     360     570     680    1020
River Rch & RM=K124-02-00,K124-02-00_0004 ,10008
     470     740     890    1360
River Rch & RM=K124-02-00,K124-02-00_0004 ,8105
     500     790     950    1450
River Rch & RM=K124-02-00,K124-02-00_0004 ,7659
     560     880    1070    1570
River Rch & RM=K124-02-00,K124-02-00_0004 ,6571
     620     950    1170    1670
River Rch & RM=K124-02-00,K124-02-00_0004 ,5672
     690    1050    1300    1800
River Rch & RM=K124-02-00,K124-02-00_0004 ,4726
     740    1140    1390    1960
River Rch & RM=K124-02-00,K124-02-00_0004 ,3195
     790    1220    1460    2090
River Rch & RM=K124-02-00,K124-02-00_0004 ,2118
     857    1338    1577    2298
Boundary for River Rch & Prof#=K124-02-00,K124-02-00_0004 , 1
Up Type= 0
Dn Type= 3
Dn Slope=.0064
Boundary for River Rch & Prof#=K124-02-00,K124-02-00_0004 , 2
Up Type= 0
Dn Type= 3
Dn Slope=.0064
Boundary for River Rch & Prof#=K124-02-00,K124-02-00_0004 , 3
Up Type= 0
Dn Type= 3
Dn Slope=.0064
Boundary for River Rch & Prof#=K124-02-00,K124-02-00_0004 , 4
Up Type= 0
Dn Type= 3
Dn Slope=.0064
DSS Import GetInterval= 0
DSS Import GetPeak= 0
DSS Import FillOption= 0

--- K124-02-00.g01 (geometry) ---

Geom Title=K124-02-00 May 2016
Version=Version 3.0.1  May 2012

River Reach=K124-02-00      ,K124-02-00_0004
Reach XY= 30
      3085676.95     13959357.13      3085671.01     13958122.34
      3085823.13      13958016.8      3085833.25       13957850.
      3085881.41     13957674.02      3086770.23     13956256.51
      3086970.97     13955723.62        3087018.       13955499.
      3087000.09     13955363.99      3086800.21     13954884.04
      3086679.55     13954667.03      3086319.31     13954162.69
      3086142.23     13954040.29      3085718.62     13954016.85
      3085651.78     13953980.39      3085733.14     13951771.34
      3085707.33     13951646.19      3085652.64      13951507.3
      3085467.75     13951220.85       3085417.4     13951097.58
      3085416.53     13950993.41      3085601.86      13949987.8
      3085644.94     13949696.38      3085651.32     13949523.48
      3085475.11     13948447.96      3085583.25       13947849.
      3085815.75       13947373.       3085861.9     13946996.57
      3085836.22     13946834.46      3085832.58      13946277.7

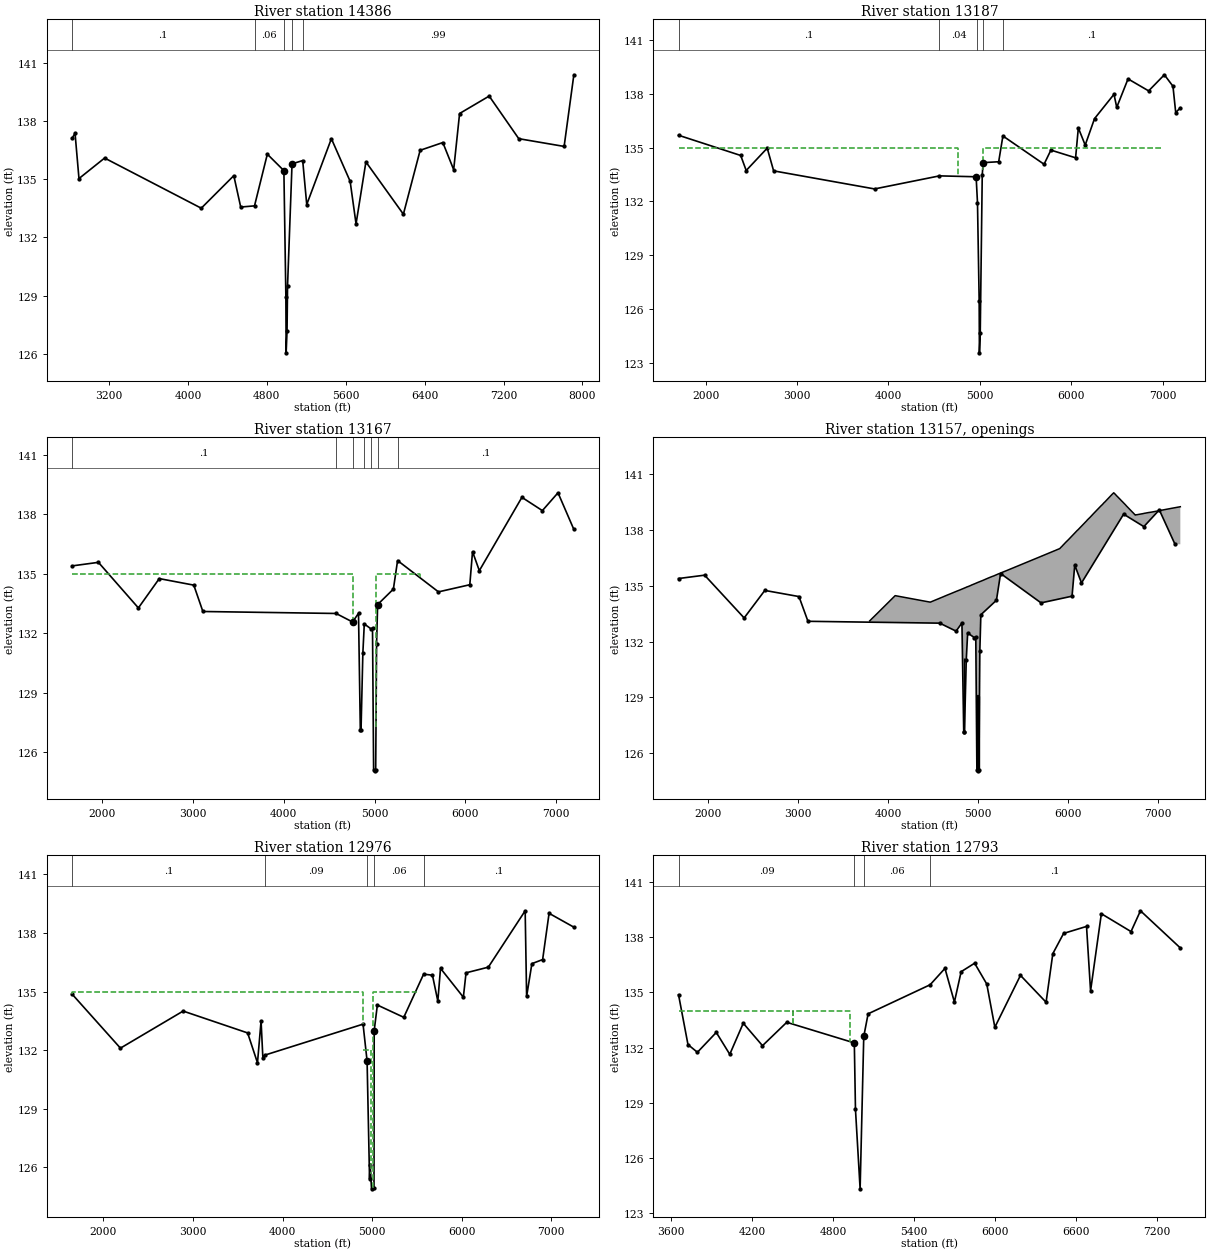
Type RM Length L Ch R = 1 ,14386   ,1200,1199,1191.5
BEGIN DESCRIPTION:
Cross Section K124-02-00-X07a
END DESCRIPTION:
XS GIS Cut Line= 4
      3087627.66     13960311.54      3085707.48     13959356.79
      3085642.29     13959357.13      3083048.62     13958108.21
#Sta/Elev= 30
    2825  137.11    2855  137.39    2895  135.04    3155   136.1    4135  133.51
    4465  135.19    4535  133.57    4675  133.63    4805   136.3  4972.9  135.45
    4993  128.94  4995.8  126.04  5004.8  127.16    5010   129.5  5055.5   135.8
 5163.59  135.97  5204.6   133.7  5454.6   137.1  5644.6   134.9  5704.6   132.7
  5804.6   135.9  6184.6   133.2  6354.6   136.5  6584.6   136.9  6694.6   135.5
  6754.6   138.4  7054.6   139.3  7354.6   137.1  7814.6   136.7  7913.3   140.4
#Mann= 5 ,-1 , 0
    2825      .1       0    4675     .06       0  4972.9     .04       0
  5055.5     .06       0 5163.59     .99       0
#XS Ineff= 2 , 0
       0  4963.2  135.35               0
Permanent Ineff=
       F       F
#Block Obstruct= 2 , 0
                         5171.83          135.96
Bank Sta=4972.9,5055.5
XS Rating Curve= 0
Exp/Cntr=.3,.1

Type RM Length L Ch R = 1 ,13187   ,46.2,20,19
BEGIN DESCRIPTION:
S5A_SPRING STUEBNER - XS4   Note:
The higher flows appear to spill towards the east and outside of the watershed.  Flows on the left overbank are modeled as ineffective in the RAS model.  The mapping has been truncated to the limit of the watershed.
END DESCRIPTION:
XS GIS Cut Line= 5
      3087621.26     13960206.47      3086819.01     13958218.37
      3085729.59     13958158.21      3085642.78      13958158.4
        3083477.     13958161.95
#Sta/Elev= 30
  1704.9   135.7  2384.9  134.57  2444.9  133.73  2674.9  134.98  2744.9  133.71
  3848.8   132.7  4558.8  133.43  4959.8  133.38 4974.75  131.92    4993  126.44
  4995.8  123.54  5004.8  124.66  5026.7  133.49  5036.7  134.17  5206.5  134.22
  5252.7  135.66  5702.7  134.08  5777.7  134.87  6047.7  134.44  6077.7  136.11
  6152.7  135.15  6254.8  136.63  6467.7  137.99  6497.7  137.26  6621.3  138.85
  6846.6  138.18  7018.6  139.08  7112.7  138.44  7142.7  136.97  7193.2  137.23
#Mann= 5 ,-1 , 0
  1704.9      .1       0  4558.8     .04       0 4974.75     .04       0
  5036.7     .06       0  5252.7      .1       0
#XS Ineff= 2 ,-1
  1704.9  4757.5     135 5030.73    7000     135
Permanent Ineff=
       F       F
Bank Sta=4959.8,5036.7
XS Rating Curve= 0
Exp/Cntr=.5,.3

Type RM Length L Ch R = 1 ,13167   ,95,191,236.7
BEGIN DESCRIPTION:
S5A_SPRING STUEBNER - XS3   Note:
The higher flows appear to spill towards the east and outside of the watershed.  Flows on the left overbank are modeled as ineffective in the RAS model.  The mapping has been truncated to the limit of the watershed.
END DESCRIPTION:
XS GIS Cut Line= 5
      3087654.41     13960178.84      3086872.67     13958201.28
      3085729.59     13958138.21      3085642.78      13958138.4
        3083477.     13958141.95
#Sta/Elev= 30
  1669.4  135.39  1959.4  135.57  2399.4  133.27  2629.4  134.75  3009.4  134.42
  3109.4  133.09  4575.9  132.99  4757.5  132.56 4822.51     133 4842.51  127.13
 4850.51  127.13 4870.51     131 4886.25  132.46 4961.55  132.21 4976.62  132.24
 4988.92  125.09 5006.62  125.05 5011.62  125.09 5021.62  131.47 5033.02  133.44
  5206.5  134.22  5252.7  135.66  5702.7  134.08  6047.7  134.44  6077.7  136.11
  6152.7  135.15  6621.3  138.85  6846.6  138.18  7018.6  139.08  7193.2  137.23
#Mann= 7 ,-1 , 0
  1669.4      .1       0  4575.9     .04       0  4757.5     .04       0
 4886.25     .06       0 4961.55     .04       0 5033.02     .06       0
  5252.7      .1       0
#XS Ineff= 3 ,-1
  1669.4  4757.5     135  4757.5 4886.25     132    5015    5500     135
Permanent Ineff=
       F       F       F
Bank Sta=4757.5,5033.02
XS Rating Curve= 0
Exp/Cntr=.5,.3

Type RM Length L Ch R = 4 ,13157   ,,,
BEGIN DESCRIPTION:
SPRING STUEBNER
Structure ID: K124-02-00-S5A; relief structure on left 10/28/02 VRR
Left overbank flow not part of stream flow
END DESCRIPTION:
Bridge Culvert--1,0,-1,-1, 0
Deck Dist Width WeirC Skew NumUp NumDn MinLoCord MaxHiCord MaxSubmerge Is_Ogee
10,174,2.6,0, 98, 98, , , .95, 0, ,,,
  3795.9  3822.4  3839.4  3839.7  4079.7  4123.3  4380.1  4470.2  4605.3    4649
    4705    4760    4807    4866    4879    4892    4912    4922    4929    4945
    4960    5004    5056    5108    5153  5176.3  5228.8  5321.2  5711.9  5713.9
  5716.4  5726.8  5776.4  5786.3  5806.4  5836.4  5845.9  5851.4  5857.1  5875.7
  5911.4  5920.3  5926.4  5935.2  5950.1  5956.4    5978  5986.4  6009.6  6106.4
  6113.8  6211.4    6218  6241.4  6247.8  6286.4  6292.4  6316.4  6322.2  6376.5
  6381.8  6391.5  6396.6  6406.5  6411.5  6421.5    6492  6500.8  6511.5  6522.2
  6530.6  6541.5  6586.5  6590.2  6601.5    6605  6616.5  6634.8  6646.5  6649.7
  6661.5  6721.5  6724.1  6751.5  6753.9  6766.5  6768.8  6826.5  6828.3  6856.5
  6858.1  6901.5  6902.8  6917.6  6931.5  7051.5  7149.8  7252.4
  133.11  133.24  133.32  133.32  134.47  134.43   134.2  134.12  134.39  134.48
  134.59   134.7  134.79  134.91  134.94  134.96     135  135.02  135.04  135.07
   135.1  135.19  135.29   135.4  135.49  135.53  135.64  135.82   136.6  136.61
  136.61  136.63  136.73  136.75  136.79  136.85  136.87  136.88  136.89  136.93
     137  137.05  137.08  137.12   137.2  137.23  137.34  137.38  137.49  137.98
  138.01   138.5  138.54  138.65  138.68  138.88  138.91  139.03  139.06  139.33
  139.35   139.4  139.43  139.48   139.5  139.55  139.91  139.95     140  139.95
  139.91  139.85  139.63  139.61  139.55  139.54  139.48  139.39  139.33  139.31
  139.25  138.95  138.94   138.8  138.81  138.82  138.82  138.87  138.87   138.9
   138.9  138.94  138.94  138.95  138.96  139.07  139.16  139.25
                                                                                
                                                                                
                                                                                
                                                                                
                                                                                
                                                                                
                                                                                
                                                                                
                                                                                
                                                                
  3760.4  3822.4  3839.4  3839.7  4079.7  4123.3  4380.1  4470.2  4605.3    4649
    4705    4760    4807    4866    4879    4892    4912    4922    4929    4945
    4960    5004    5056    5108    5153  5176.3  5228.8  5321.2  5711.9  5713.9
  5716.4  5726.8  5776.4  5786.3  5806.4  5836.4  5845.9  5851.4  5857.1  5875.7
  5911.4  5920.3  5926.4  5935.2  5950.1  5956.4    5978  5986.4  6009.6  6106.4
  6113.8  6211.4    6218  6241.4  6247.8  6286.4  6292.4  6316.4  6322.2  6376.5
  6381.8  6391.5  6396.6  6406.5  6411.5  6421.5    6492  6500.8  6511.5  6522.2
  6530.6  6541.5  6586.5  6590.2  6601.5    6605  6616.5  6634.8  6646.5  6649.7
  6661.5  6721.5  6724.1  6751.5  6753.9  6766.5  6768.8  6826.5  6828.3  6856.5
  6858.1  6901.5  6902.8  6917.6  6931.5  7051.5  7149.8  7252.4
  132.77  133.24  133.32  133.32  134.47  134.43   134.2  134.12  134.39  134.48
  134.59   134.7  134.79  134.91  134.94  134.96     135  135.02  135.04  135.07
   135.1  135.19  135.29   135.4  135.49  135.53  135.64  135.82   136.6  136.61
  136.61  136.63  136.73  136.75  136.79  136.85  136.87  136.88  136.89  136.93
     137  137.05  137.08  137.12   137.2  137.23  137.34  137.38  137.49  137.98
  138.01   138.5  138.54  138.65  138.68  138.88  138.91  139.03  139.06  139.33
  139.35   139.4  139.43  139.48   139.5  139.55  139.91  139.95     140  139.95
  139.91  139.85  139.63  139.61  139.55  139.54  139.48  139.39  139.33  139.31
  139.25  138.95  138.94   138.8  138.81  138.82  138.82  138.87  138.87   138.9
   138.9  138.94  138.94  138.95  138.96  139.07  139.16  139.25
                                                                                
                                                                                
                                                                                
                                                                                
                                                                                
                                                                                
                                                                                
                                                                                
                                                                                
                                                                
BR Coef= 0 , 0 , 0 ,1.25, 0 ,,,.8,-1,2,0,
WSPro=,,,, 1 ,,,, 0 ,,,, 0 ,,,,-1 ,-1 ,-1 , 0 , 0 , 0 , 0 , 0
BR Coef= 1 , 0 , 0 ,1.25, 0 ,,,.8,-1,2,0,
WSPro=,,,, 1 ,,,, 0 ,,,, 0 ,,,,-1 ,-1 ,-1 , 0 , 0 , 0 , 0 , 0
Culvert=2,4,8,85,.013,.2,1,11,4,127.13,4846.51,127.04,4971.5,Culvert #1  , 0 ,1
Culvert Bottom n=.013
Culvert=2,4,8,174,.015,.5,1,8,1,125.11,4993.52,124.89,4993.52,Culvert #2  , 0 ,10
Culvert Bottom n=.015
Culvert=2,4,8,174,.015,.5,1,8,1,125.05,5006.62,124.91,5006.62,Culvert #3  , 0 ,10
Culvert Bottom n=.015
BC Mult= 2 ,385.7,4961.55,339.2,4985
BC Mult= 2 ,4886.25,7193.2,4977,7252.4
BC Design=,, 0 ,, 0 ,,,,,,
BC HTab HWMax=139.08

Type RM Length L Ch R = 1 ,12976   ,194.4,183,143.9
BEGIN DESCRIPTION:
S5A_SPRING STUEBNER - XS2   Note:
The higher flows appear to spill towards the east and outside of the watershed.  Flows on the left overbank are modeled as ineffective in the RAS model.  The mapping has been truncated to the limit of the watershed.
END DESCRIPTION:
XS GIS Cut Line= 6
        3087787.     13960112.55      3086983.71     13958109.07
      3085887.82     13958048.55      3085818.32      13958048.7
      3085814.15     13957987.98      3083598.96      13957949.6
#Sta/Elev= 30
  1650.4  134.87  2190.4   132.1  2890.4     134  3610.4  132.88  3720.4  131.35
  3760.4  133.49  3780.4  131.61  3800.4  131.74  4898.9  133.33 4944.02  131.44
  4971.5   125.4  4978.5  126.13 4993.52  124.89 5021.02  124.93 5023.25  132.99
  5058.6  134.31  5353.6  133.68  5574.8  135.89  5673.6  135.84  5733.7  134.51
  5763.7  136.19  6018.7  134.71  6048.7  135.96  6297.4  136.25  6708.8  139.14
    6725  134.75  6783.8  136.43  6903.8  136.64  6975.7  139.01  7252.4   138.3
#Mann= 5 ,-1 , 0
  1650.4      .1       0  3800.4     .09       0 4944.02     .04       0
 5023.25     .06       0  5574.8      .1       0
#XS Ineff= 3 ,-1
  1650.4    4899     135    4899    4984     132    5015    5500     135
Permanent Ineff=
       F       F       F
Bank Sta=4944.02,5023.25
XS Rating Curve= 0
Exp/Cntr=.5,.3

Type RM Length L Ch R = 1 ,12793   ,188,188,201.1
BEGIN DESCRIPTION:
S4_GREEN LAKES - XS 4   Note:
The higher flows appear to spill towards the east and outside of the watershed.  Flows on the left overbank are modeled as ineffective in the RAS model.  The mapping has been truncated to the limit of the watershed.
END DESCRIPTION:
XS GIS Cut Line= 5
      3087120.31     13957613.94      3086577.07     13957874.99
      3085876.45     13957848.02      3085794.24      13957843.4
      3083458.75     13957816.21
#Sta/Elev= 30
  3653.7  134.87  3723.7  132.16  3793.7  131.74  3933.7  132.82  4033.7  131.63
  4133.7  133.32  4276.4   132.1  4456.4  133.37  4957.5  132.25    4966  128.64
  5000.5  124.32  5027.5   132.6  5059.8  133.83  5519.8  135.41  5629.8   136.3
  5699.8  134.47  5749.8  136.12  5849.8  136.58  5939.8  135.45  5999.8   133.1
  6189.8  135.92  6379.8  134.46  6429.8   137.1  6509.8   138.2  6679.8  138.58
  6709.8  135.08  6789.8  139.27  7009.8   138.3  7079.8  139.43  7375.5  137.41
#Mann= 4 ,-1 , 0
  3653.7     .09       0  4957.5     .04       0  5027.5     .06       0
  5519.8      .1       0
#XS Ineff= 2 ,-1
    4500    4926     134  3653.7    4500     134
Permanent Ineff=
       F       F
#Block Obstruct= 2 , 0
                         5928.19             134
Bank Sta=4957.5,5027.5
XS Rating Curve= 0
Exp/Cntr=.5,.3

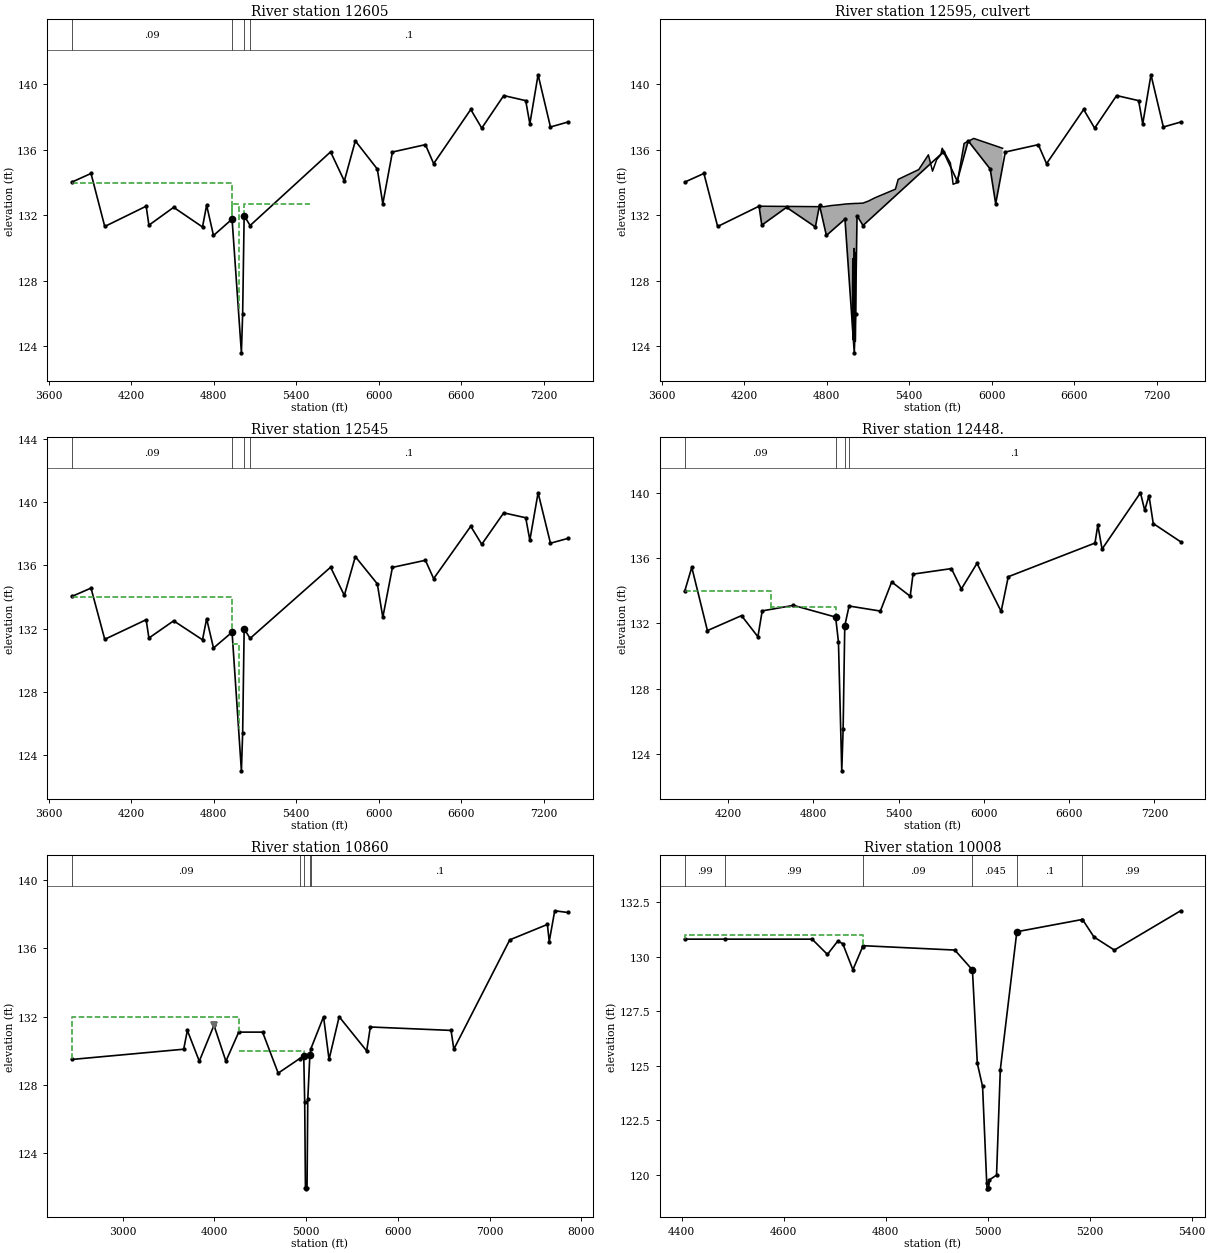
Type RM Length L Ch R = 1 ,12605   ,57.8,60,60.6
BEGIN DESCRIPTION:
S4_GREEN LAKES - XS 3   Note:
The higher flows appear to spill towards the east and outside of the watershed.  Flows on the left overbank are modeled as ineffective in the RAS model.  The mapping has been truncated to the limit of the watershed.
END DESCRIPTION:
XS GIS Cut Line= 5
      3087088.71     13957520.29      3086588.12      13957698.2
      3085928.95     13957668.51      3085846.74     13957663.89
      3083511.25      13957636.7
#Sta/Elev= 30
  3766.1  134.03  3906.1  134.56  4006.1  131.32  4307.4  132.56  4327.4   131.4
  4507.4  132.49  4717.4  131.29  4747.4  132.62  4797.4  130.77  4932.6  131.77
  5000.5   123.6  5009.6     126  5020.5  131.98    5064  131.38  5649.5  135.88
  5749.5   134.1  5829.5  136.55  5989.5  134.83  6029.5  132.71  6099.5  135.87
  6339.5  136.32  6399.5  135.16  6669.5  138.47  6749.5  137.33  6909.5  139.32
  7069.5  139.01  7099.5  137.59  7159.5  140.59  7249.5   137.4  7375.2   137.7
#Mann= 4 ,-1 , 0
  3766.1     .09       0  4932.6     .04       0  5020.5     .04       0
    5064      .1       0
#XS Ineff= 3 ,-1
  4932.6    4980   132.7  3766.1  4932.6     134  5020.5    5500   132.7
Permanent Ineff=
       F       F       F
#Block Obstruct= 2 , 0
                         6005.73          134.01
Bank Sta=4932.6,5020.5
XS Rating Curve= 0
Exp/Cntr=.5,.3

Type RM Length L Ch R = 2 ,12595   ,,,
BEGIN DESCRIPTION:
GREENLAKES
Structure ID: K124-02-00-S4
END DESCRIPTION:
Bridge Culvert--1,0,-1,-1, 0
Deck Dist Width WeirC Skew NumUp NumDn MinLoCord MaxHiCord MaxSubmerge Is_Ogee
10,49,2.6,0, 40, 40, , , .95, 0, ,,,
  4307.4  4780.1  4832.4  4832.7  4882.6  4925.1  4932.6    4966  4987.3  4995.9
  4997.9  4998.4  5000.5  5001.7  5002.1    5003  5009.6  5009.9  5020.5    5064
    5065  5070.6  5108.3  5111.8 5151.99  5152.1  5299.8  5319.8  5469.8  5539.8
  5569.8  5599.8  5629.8  5639.8  5699.8  5719.8  5749.8  5799.8  5869.8  6079.8
  132.56  132.53   132.6   132.6  132.64  132.68  132.69  132.71  132.72  132.72
  132.72  132.72  132.73  132.73  132.73  132.73  132.73  132.73  132.73  132.75
  132.75  132.77  132.89  132.91  133.08  133.08   133.6   134.2   134.8   135.7
   134.7   135.4   135.7   136.1   135.2   133.9     134   136.4   136.7   136.1
                                                                                
                                                                                
                                                                                
                                                                                
  4307.4  4780.1  4832.4  4832.7  4882.6  4925.1  4932.6    4966  4987.3  4995.9
  4997.9  4998.4  5000.5  5001.7  5002.1    5003  5009.6  5009.9  5020.5    5064
    5065  5070.6  5108.3  5111.8 5151.99  5152.1  5299.8  5319.8  5469.8  5539.8
  5569.8  5599.8  5629.8  5639.8  5699.8  5719.8  5749.8  5799.8  5869.8  6079.8
  132.56  132.53   132.6   132.6  132.64  132.68  132.69  132.71  132.72  132.72
  132.72  132.72  132.73  132.73  132.73  132.73  132.73  132.73  132.73  132.75
  132.75  132.77  132.89  132.91  133.08  133.08   133.6   134.2   134.8   135.7
   134.7   135.4   135.7   136.1   135.2   133.9     134   136.4   136.7   136.1
                                                                                
                                                                                
                                                                                
                                                                                
BR Coef= 1 , 1 , 1 ,1.25, 0 ,,,.8,0,2,0,
WSPro=,,,, 1 ,,,, 0 ,,,, 0 ,,,,-1 ,-1 ,-1 , 0 , 0 , 0 , 0 , 0
Culvert=1,5,,49,.014,.4,1,1,3,124.38,4990,123.44,4990,Culvert #1  , 0 ,10
Culvert Bottom n=.014
Culvert=1,5.5,,49,.014,.4,1,1,3,124.51,5000,123,5000,Culvert #2  , 0 ,10
Culvert Bottom n=.014
Culvert=1,5.5,,49,.014,.4,1,1,3,124.26,5008.5,123.36,5008.5,Culvert #3  , 0 ,10
Culvert Bottom n=.014
BC Design=,, 0 ,, 0 ,,,,,,
BC HTab HWMax=140.6

Type RM Length L Ch R = 1 ,12545   ,82.6,97,115.4
BEGIN DESCRIPTION:
S4_GREEN LAKES - XS 2
END DESCRIPTION:
XS GIS Cut Line= 5
        3087074.     13957480.79      3086599.17      13957631.9
      3085952.43      13957617.5       3085867.3     13957612.73
      3083531.37     13957585.53
#Sta/Elev= 30
  3766.1  134.03  3906.1  134.56  4006.1  131.32  4307.4  132.56  4327.4   131.4
  4507.4  132.49  4717.4  131.29  4747.4  132.62  4797.4  130.77  4932.6  131.77
  5000.5     123  5009.6   125.4  5020.5  131.98    5064  131.38  5649.5  135.88
  5749.5   134.1  5829.5  136.55  5989.5  134.83  6029.5  132.71  6099.5  135.87
  6339.5  136.32  6399.5  135.16  6669.5  138.47  6749.5  137.33  6909.5  139.32
  7069.5  139.01  7099.5  137.59  7159.5  140.59  7249.5   137.4  7375.2   137.7
#Mann= 4 ,-1 , 0
  3766.1     .09       0  4932.6     .04       0  5020.5     .04       0
    5064      .1       0
#XS Ineff= 3 ,-1
  4932.6    4980     131  3766.1  4932.6     134  5020.5    5500     131
Permanent Ineff=
       F       F       F
#Block Obstruct= 2 , 0
                         5983.29          134.87
Bank Sta=4932.6,5020.5
XS Rating Curve= 0
Exp/Cntr=.5,.3

Type RM Length L Ch R = 1 ,12448.  ,1590.5,1588,1593.2
BEGIN DESCRIPTION:
S4_GREEN LAKES - XS 1
LIDAR overbanks, Interpolated channel
END DESCRIPTION:
XS GIS Cut Line= 5
      3087042.45     13957414.22      3086593.64     13957571.13
      3086007.44      13957551.1      3085930.48     13957515.58
       3083588.2     13957479.93
#Sta/Elev= 30
  3895.2  133.97  3945.2  135.45  4055.2  131.56  4295.2  132.48  4410.6  131.18
  4440.6  132.77  4660.6  133.11  4957.2  132.39  4977.2  130.86 5000.45  122.94
 5010.07  125.51 5021.59  131.85  5051.9  133.07  5271.9  132.76  5351.9  134.55
  5481.9  133.67  5501.9  135.03  5771.9  135.37  5841.9  134.12  5951.9  135.69
  6121.9  132.74  6171.9  134.87  6781.9  136.94  6801.9  138.04  6831.9  136.57
  7101.9  140.03  7131.9  138.95  7161.9  139.86  7191.9  138.14  7384.5  137.02
#Mann= 4 ,-1 , 0
  3895.2     .09       0  4957.2     .04       0 5021.59     .04       0
  5051.9      .1       0
#XS Ineff= 2 ,-1
    4500  4957.2     133  3895.2    4500     134
Permanent Ineff=
       F       F
Bank Sta=4957.2,5021.59
XS Rating Curve= 0
Exp/Cntr=.3,.1

Type RM Length L Ch R = 1 ,10860   ,884.4,852,826.6
BEGIN DESCRIPTION:
Cross Section K124-02-00-X6
END DESCRIPTION:
XS GIS Cut Line= 4
      3089192.17       13957093.      3086859.17     13956207.15
       3086777.5     13956171.98      3083970.82      13956463.6
#Sta/Elev= 30
  2444.3   129.5  3664.3   130.1  3704.3   131.2  3834.3   129.4  3994.3   131.5
  4124.3   129.4  4264.3   131.1  4524.3   131.1  4694.3   128.7    4928  129.55
  4972.9   129.7  4983.3     127  4991.3  121.97  4999.7  121.93  5008.7  121.98
  5016.9  127.16  5039.5  129.75  5051.6  130.14  5188.8     132  5248.8   129.5
  5358.8     132  5658.8     130  5698.8   131.4  6578.8   131.2  6608.8   130.1
  7218.8   136.5  7628.8   137.4  7648.8   136.4  7708.8   138.2  7850.5   138.1
#Mann= 5 ,-1 , 0
  2444.3     .09       0    4928     .06       0  4972.9     .04       0
  5039.5    .045       0  5051.6      .1       0
Levee=-1,3994.3,131.5,0,,,,
#XS Ineff= 3 ,-1
  2444.3  4264.3     132  4264.3  4972.9     130  5188.8    7000     132
Permanent Ineff=
       F       F       F
#Block Obstruct= 2 , 0
                         6580.28          131.28
Bank Sta=4972.9,5039.5
XS Rating Curve= 0
Exp/Cntr=.3,.1

Type RM Length L Ch R = 1 ,10008   ,1996,1903,1814
BEGIN DESCRIPTION:
Cross Section K124-02-00-X5
END DESCRIPTION:
XS GIS Cut Line= 4
 3087586.210988913955263.3777921      3087064.12      13955356.8
      3086795.84      13955404.8 3086631.946576213955449.6927632
#Sta/Elev= 27
  4405.7   130.8  4485.3   130.8  4655.7   130.8  4685.7   130.1  4705.7   130.7
  4715.7   130.6  4735.7   129.4    4755  130.46  4755.7   130.5  4935.7   130.3
  4970.2  129.39  4979.8  125.11  4990.1  124.05  4998.2  119.64  4998.8  119.36
  4999.9  119.37  5001.4  119.38  5001.8  119.39  5003.6  119.77  5017.5  119.99
  5024.9  124.82  5057.3  131.14  5185.4   131.7  5186.1   131.7  5208.6   130.9
  5248.6   130.3  5378.6   132.1
#Mann= 6 ,-1 , 0
  4405.7     .99       0  4485.3     .99       0    4755     .09       0
  4970.2    .045       0  5057.3      .1       0  5185.4     .99       0
#XS Ineff= 2 , 0
       0  4755.7     131               0
Permanent Ineff=
       F       F
Bank Sta=4970.2,5057.3
XS Rating Curve= 0
Exp/Cntr=.3,.1

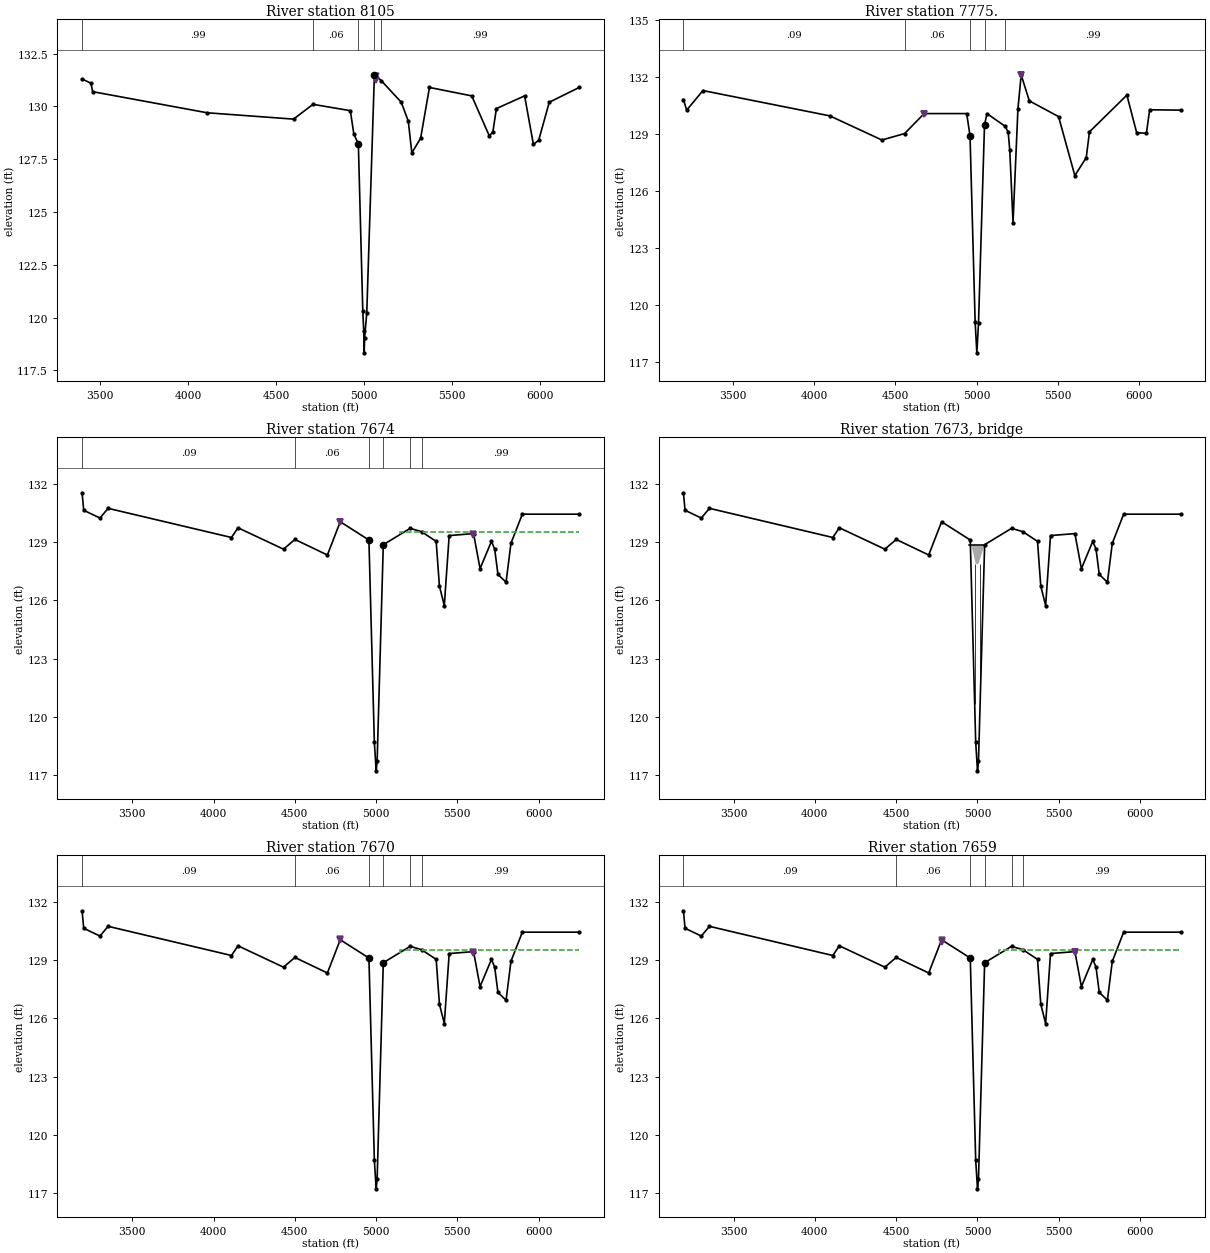
Type RM Length L Ch R = 1 ,8105    ,262.4,330,419.3
BEGIN DESCRIPTION:
Cross Section K124-02-00-X03
High points on far left shown on contours, homes back up into this area as well 10/25/02 VRR
END DESCRIPTION:
XS GIS Cut Line= 5
 3087292.529297113954007.7423849      3085847.33     13953864.01
       3085845.8     13953960.25      3085854.14     13954052.77
 3084922.897293913954777.3763854
#Sta/Elev= 30
  3398.6   131.3  3448.6   131.1  3458.6   130.7  4108.6   129.7  4598.6   129.4
  4709.2   130.1  4920.9   129.8  4940.9   128.7  4966.6  128.22  4991.8  120.29
  4997.1  119.35  4999.9  118.33    5002  119.04  5014.3  120.22  5057.6   131.5
    5097  131.22  5210.1   130.2  5250.1   129.3  5270.1   127.8  5320.1   128.5
  5370.1   130.9  5610.1   130.5  5710.1   128.6  5730.1   128.8  5750.1   129.9
  5910.1   130.5  5960.1   128.2  5990.1   128.4  6050.1   130.2  6220.1   130.9
#Mann= 5 ,-1 , 0
  3398.6     .99       0  4709.2     .06       0  4966.6    .045       0
  5057.6     .06       0    5097     .99       0
Levee=0,,,-1,5067.05,131.25,,
Bank Sta=4966.6,5057.6
XS Rating Curve= 0
Exp/Cntr=.3,.1

Type RM Length L Ch R = 1 ,7775.   ,100.6,101,101.6
BEGIN DESCRIPTION:
PL U/S OF FM2920- XS 4
LIDAR overbanks, Interpolated channel
END DESCRIPTION:
XS GIS Cut Line= 5
      3087442.73     13953985.08      3085809.33     13953820.03
      3085709.32     13953864.71      3085614.16     13953862.06
      3084636.18     13954574.43
#Sta/Elev= 30
  3196.4  130.81  3216.4  130.25  3316.4  131.28  4096.4  129.95  4416.4  128.68
  4556.4  129.02  4676.4  130.07  4938.1  130.07 4958.48  128.89 4989.91   119.1
 5000.36  117.49 5010.56  119.05 5047.49  129.48  5062.8  130.07  5172.8  129.41
  5192.8  129.11  5202.8  128.14  5222.8  124.34  5252.8  130.29  5272.8  132.11
  5322.8  130.74  5502.8  129.91  5602.8  126.81  5672.8  127.75  5692.8  129.11
  5922.8  131.04  5982.8  129.07  6042.8  129.03  6062.8  130.27  6252.8  130.25
#Mann= 5 ,-1 , 0
  3196.4     .09       0  4556.4     .06       0 4958.48     .04       0
 5047.49     .06       0  5172.8     .99       0
Levee=-1,4676.4,130.07,-1,5272.8,132.11,,
#XS Ineff= 2 , 0
       0 4849.94   129.5 5149.65       0   129.5
Permanent Ineff=
       F       F
Bank Sta=4958.48,5047.49
XS Rating Curve= 0
Exp/Cntr=.5,.3

Type RM Length L Ch R = 1 ,7674    ,3.2,4,3.2
BEGIN DESCRIPTION:
PL U/S OF FM2920- XS 3
END DESCRIPTION:
XS GIS Cut Line= 5
 3087453.264333413953942.3743126      3086797.48      13953876.8
      3085709.31       13953763.      3085614.16      13953760.4
 3084636.180434813954472.8191577
#Sta/Elev= 30
  3191.4  131.53  3201.4  130.63  3301.4  130.23  3351.4  130.73  4110.5  129.23
  4150.5  129.73  4430.5  128.63  4500.5  129.13  4700.5  128.33  4779.6  130.04
    4956   129.1  4989.4  118.71  5000.5  117.23  5006.5  117.72  5044.4  128.86
  5209.8   129.7  5279.7  129.53  5369.7  129.03  5389.7  126.73  5419.7  125.73
  5449.7  129.33  5599.7  129.43  5639.7  127.63  5709.7  129.03  5729.7  128.63
  5749.7  127.33  5799.7  126.93  5829.7  128.93  5899.7  130.43  6249.7  130.43
#Mann= 6 ,-1 , 0
  3191.4     .09       0  4500.5     .06       0    4956     .04       0
  5044.4     .06       0  5209.8      .1       0  5279.7     .99       0
Levee=-1,4777.98,130.01,-1,5598.58,129.36,,
#XS Ineff= 2 , 0
       0 4849.94   129.5 5149.65       0   129.5
Permanent Ineff=
       F       F
Bank Sta=4956,5044.4
XS Rating Curve= 0
Exp/Cntr=.5,.3

Type RM Length L Ch R = 3 ,7673    ,,,
BEGIN DESCRIPTION:
PL US of FM 2920
END DESCRIPTION:
Bridge Culvert--1,0,-1,-1, 0
Deck Dist Width WeirC Skew NumUp NumDn MinLoCord MaxHiCord MaxSubmerge Is_Ogee
1,1,2.6,0, 2, 2, , , .95, 0, 0,0,,
  4950.3    5054
  128.87  128.87
  127.87  127.87
  4950.3    5054
  128.87  128.87
  127.87  127.87
Pier Skew, UpSta & Num, DnSta & Num=  ,4983.1, 2 ,4983.1, 2 , 0 , 0 , 0 ,,
       1       1
     116   128.4
       1       1
     116   128.4
Pier Skew, UpSta & Num, DnSta & Num=  ,5016.7, 2 ,5016.7, 2 , 0 , 0 , 0 ,,
       1       1
     116   128.4
       1       1
     116   128.4
BR Coef=-1 , 1 , 1 ,1.25, 0 ,,,.8,0,2,0,
WSPro=,,,, 1 ,,,, 0 ,,,, 0 ,,,,-1 ,-1 ,-1 , 0 , 0 , 0 , 0 , 0
BC Design=,, 0 ,, 0 ,,,,,,
BC HTab HWMax=131.53

Type RM Length L Ch R = 1 ,7670    ,10,11,12
BEGIN DESCRIPTION:
PL U/S OF FM2920- XS 2
END DESCRIPTION:
XS GIS Cut Line= 5
 3087455.154261613953939.1750307      3086799.36      13953873.6
       3085711.2      13953759.9      3085616.05      13953757.3
 3084638.070434813954469.7191577
#Sta/Elev= 30
  3191.4  131.53  3201.4  130.63  3301.4  130.23  3351.4  130.73  4110.5  129.23
  4150.5  129.73  4430.5  128.63  4500.5  129.13  4700.5  128.33  4779.6  130.04
    4956   129.1  4989.4  118.71  5000.5  117.23  5006.5  117.72  5044.4  128.86
  5209.8   129.7  5279.7  129.53  5369.7  129.03  5389.7  126.73  5419.7  125.73
  5449.7  129.33  5599.7  129.43  5639.7  127.63  5709.7  129.03  5729.7  128.63
  5749.7  127.33  5799.7  126.93  5829.7  128.93  5899.7  130.43  6249.7  130.43
#Mann= 6 ,-1 , 0
  3191.4     .09       0  4500.5     .06       0    4956     .04       0
  5044.4     .06       0  5209.8      .1       0  5279.7     .99       0
Levee=-1,4781.08,130.06,-1,5598.58,129.36,,
#XS Ineff= 2 , 0
       0 4853.94   129.5 5145.65       0   129.5
Permanent Ineff=
       F       F
Bank Sta=4956,5044.4
XS Rating Curve= 0
Exp/Cntr=.5,.3

Type RM Length L Ch R = 1 ,7659    ,99.6,99,98
BEGIN DESCRIPTION:
S8_FM2920 - XS 3
END DESCRIPTION:
XS GIS Cut Line= 5
 3087456.462179313953928.2958558      3086800.68     13953862.73
      3085712.52       13953749.      3085617.36     13953746.36
 3084639.398662213954458.7441799
#Sta/Elev= 30
  3191.4  131.53  3201.4  130.63  3301.4  130.23  3351.4  130.73  4110.5  129.23
  4150.5  129.73  4430.5  128.63  4500.5  129.13  4700.5  128.33  4779.6  130.04
    4956   129.1  4989.4  118.71  5000.5  117.23  5006.5  117.72  5044.4  128.86
  5209.8   129.7  5279.7  129.53  5369.7  129.03  5389.7  126.73  5419.7  125.73
  5449.7  129.33  5599.7  129.43  5639.7  127.63  5709.7  129.03  5729.7  128.63
  5749.7  127.33  5799.7  126.93  5829.7  128.93  5899.7  130.43  6249.7  130.43
#Mann= 6 ,-1 , 0
  3191.4     .09       0  4500.5     .06       0    4956     .04       0
  5044.4     .06       0  5209.8      .1       0  5279.7     .99       0
Levee=-1,4781.08,129.95,-1,5598.58,129.41,,
#XS Ineff= 2 , 0
       0 4864.94   129.5 5134.65       0   129.5
Permanent Ineff=
       F       F
Bank Sta=4956,5044.4
XS Rating Curve= 0
Exp/Cntr=.5,.3