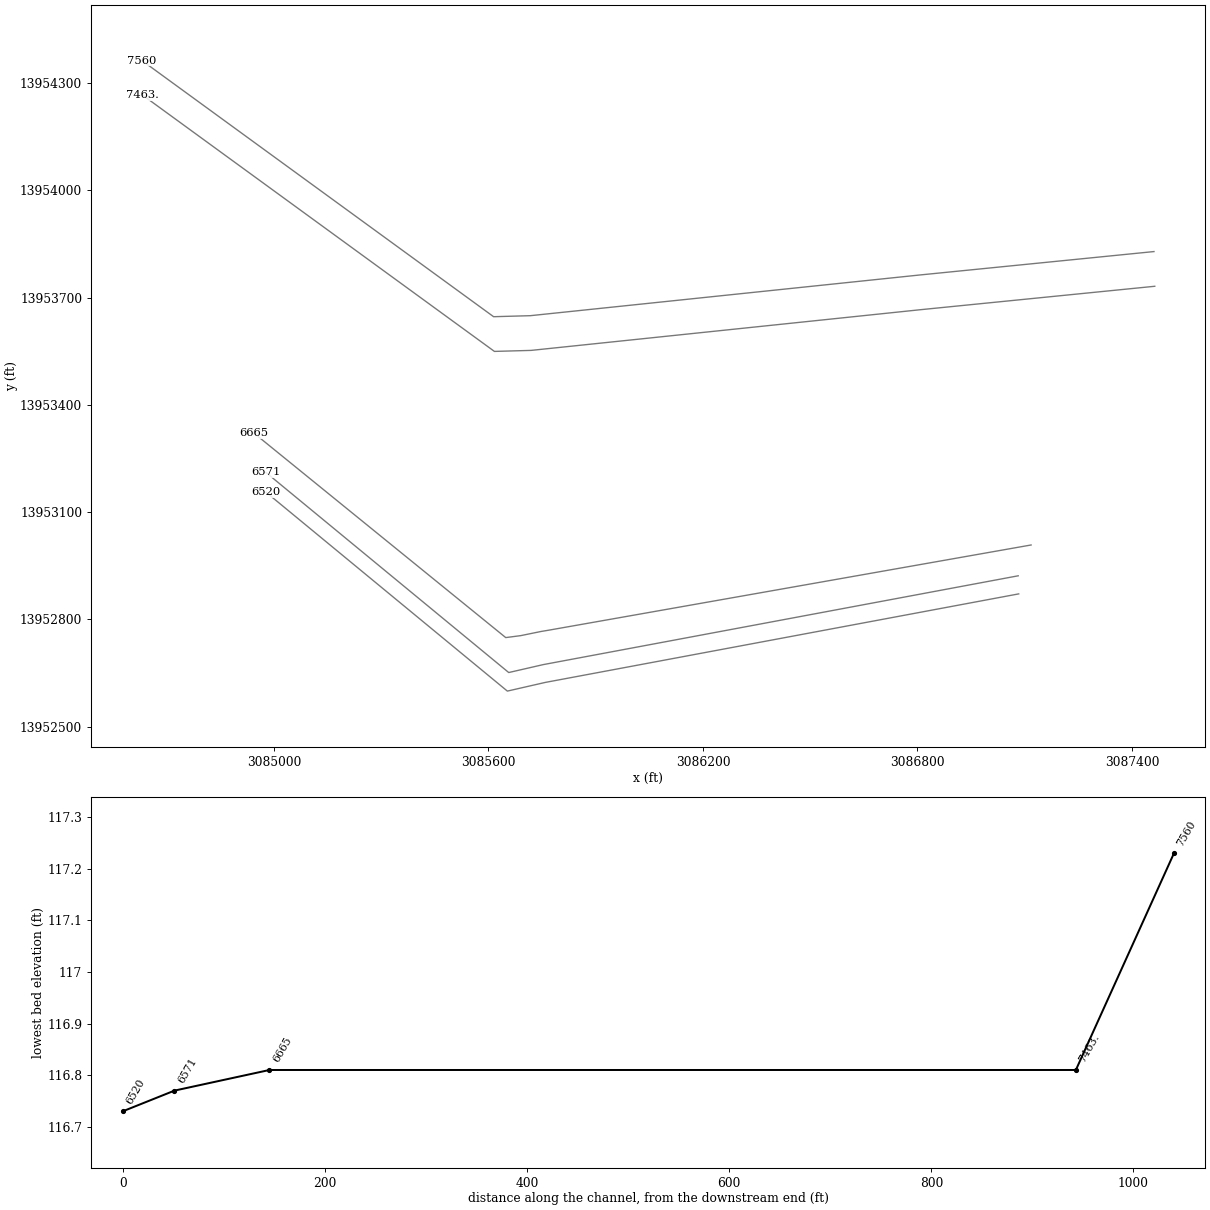
HEC-RAS study K124-02-00.prj: K124-02-00

--- K124-02-00.g01 (geometry) --- (continued)

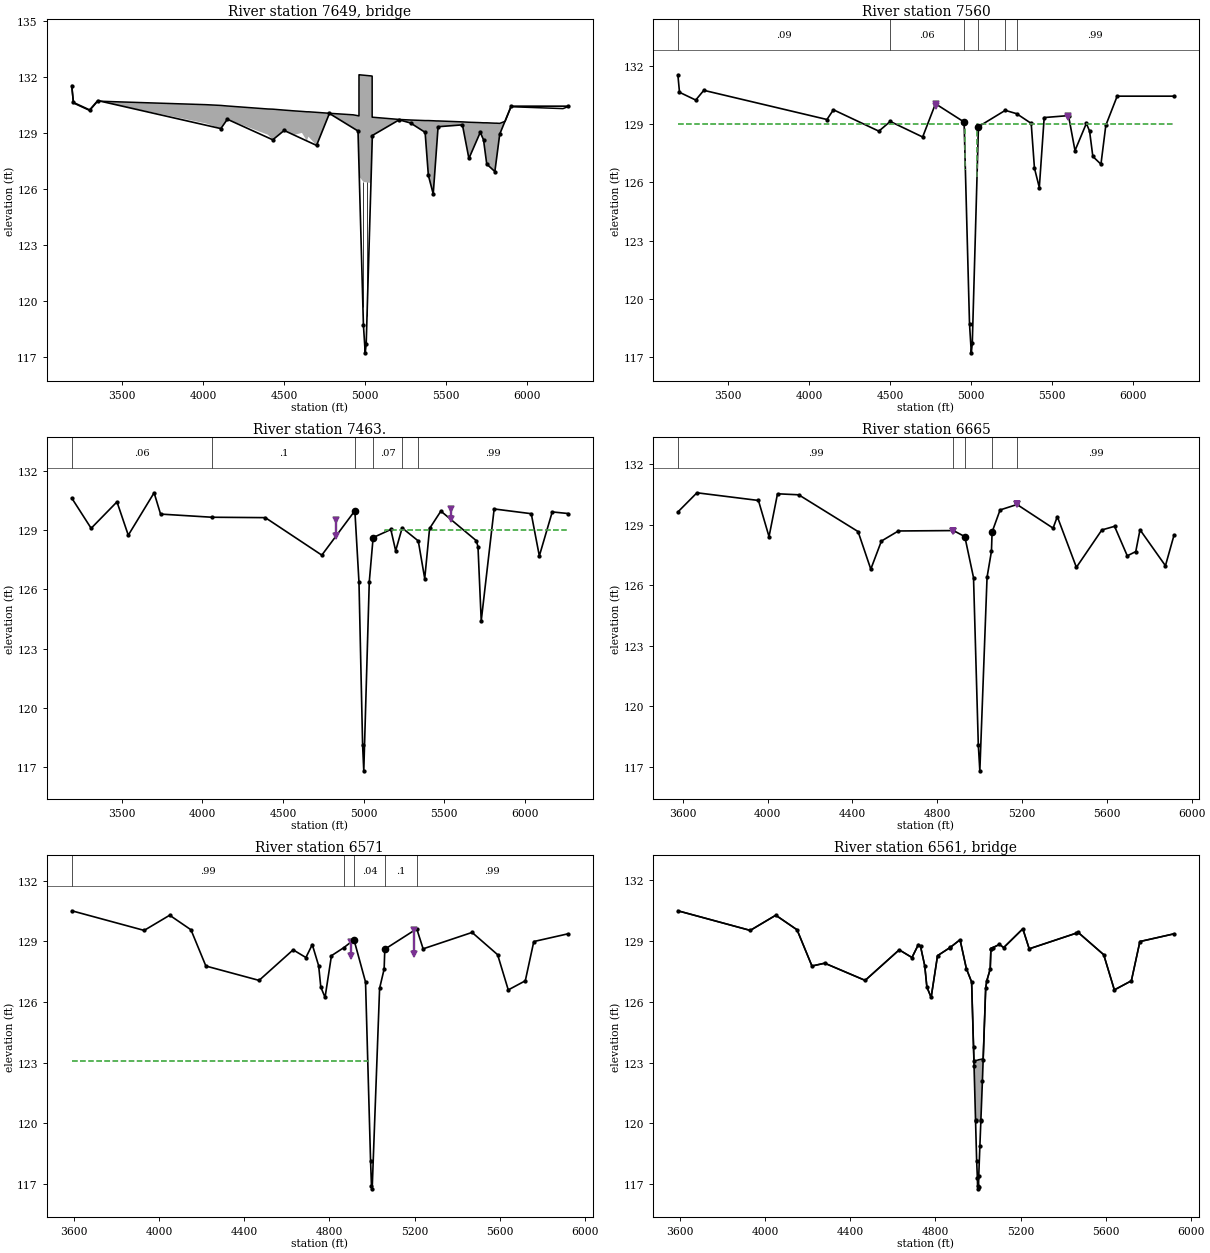
Type RM Length L Ch R = 3 ,7649    ,,,
BEGIN DESCRIPTION:
FM2920
Structure ID: K124-02-00-S8
END DESCRIPTION:
Bridge Culvert--1,0,-1,-1, 0
Deck Dist Width WeirC Skew NumUp NumDn MinLoCord MaxHiCord MaxSubmerge Is_Ogee
10,82,2.6,0, 46, 46, , , .95, 0, ,,,
  3191.4  3201.4  3301.4  3351.4  3451.4  4020.5  4110.5  4150.5  4400.5  4430.5
  4500.5  4560.5  4610.5  4640.5  4650.5  4700.5  4779.6    4921  4924.6    4956
 4961.89    4962 4963.85  5035.7  5043.2 5043.31  5044.4  5209.8  5279.7  5369.7
  5389.7  5419.7  5439.7  5449.7  5599.7  5639.7  5709.7  5729.7  5749.7  5799.7
  5809.7  5829.7    5863  5899.7  6219.7  6249.7
   131.5   130.6   130.2   130.7  130.67  130.51  130.47  130.44  130.28  130.27
  130.22  130.18  130.15  130.13  130.13   130.1  130.05  129.97  129.97  129.92
  129.91  132.11  132.11  132.05  132.04  129.84  129.84  129.72  129.69  129.66
  129.66  129.65  129.64  129.64  129.59  129.57  129.55  129.54  129.54  129.52
  129.52  129.51  129.62   130.4   130.3   130.4
   131.5   130.6   130.2   130.7   130.4   129.5   129.2   129.7   128.9   128.6
   129.1   128.8     129   128.4   128.8   128.3  130.01  129.29  129.12  129.07
  127.07  127.04  126.41  126.32  128.48  128.51  128.83  129.67   129.5     129
   126.7   125.7   128.4   129.3   129.4   127.6     129   128.6   127.3   126.9
   127.4   128.9  129.61   130.4   130.3   130.4
  3191.4  3201.4  3301.4  3351.4  3451.4  4020.5  4110.5  4150.5  4400.5  4430.5
  4500.5  4560.5  4610.5  4640.5  4650.5  4700.5  4779.6    4921  4924.6    4956
 4961.89    4962 4963.85  5035.7  5043.2 5043.31  5044.4  5209.8  5279.7  5369.7
  5389.7  5419.7  5439.7  5449.7  5599.7  5639.7  5709.7  5729.7  5749.7  5799.7
  5809.7  5829.7    5863  5899.7  6219.7  6249.7
   131.5   130.6   130.2   130.7  130.67  130.51  130.47  130.44  130.28  130.27
  130.22  130.18  130.15  130.13  130.13   130.1  130.05  129.97  129.97  129.92
  129.91  132.11  132.11  132.05  132.04  129.84  129.84  129.72  129.69  129.66
  129.66  129.65  129.64  129.64  129.59  129.57  129.55  129.54  129.54  129.52
  129.52  129.51  129.62   130.4   130.3   130.4
   131.5   130.6   130.2   130.7   130.4   129.5   129.2   129.7   128.9   128.6
   129.1   128.8     129   128.4   128.8   128.3  130.01  129.29  129.12  129.07
  127.07  127.04  126.41  126.32  128.48  128.51  128.83  129.67   129.5     129
   126.7   125.7   128.4   129.3   129.4   127.6     129   128.6   127.3   126.9
   127.4   128.9  129.61   130.4   130.3   130.4
Pier Skew, UpSta & Num, DnSta & Num=  ,4986.3, 2 ,4986.3, 2 , 0 , 0 , 0 ,,
     1.3     1.3
  118.66  127.39
     1.3     1.3
  119.16  127.89
Pier Skew, UpSta & Num, DnSta & Num=  ,5011.5, 2 ,5011.5, 2 , 0 , 0 , 0 ,,
     1.3     1.3
  118.06  127.37
     1.3     1.3
  118.56  127.87
BR Coef= 1 , 1 , 1 ,1.25, 0 ,,,.8,0,2,0,
WSPro=,,,, 1 ,,,, 0 ,,,, 0 ,,,,-1 ,-1 ,-1 , 0 , 0 , 0 , 0 , 0
BC Design=,, 0 ,, 0 ,,,,,,
BC HTab HWMax=131.53

Type RM Length L Ch R = 1 ,7560    ,96,97,98
BEGIN DESCRIPTION:
S8_FM2920 - XS 2
END DESCRIPTION:
XS GIS Cut Line= 5
 3087461.6754105 13953828.863541      3086805.94     13953763.29
      3085717.06     13953649.49      3085614.32     13953646.63
 3084630.843718513954363.0373931
#Sta/Elev= 30
  3191.4  131.53  3201.4  130.63  3301.4  130.23  3351.4  130.73  4110.5  129.23
  4150.5  129.73  4430.5  128.63  4500.5  129.13  4700.5  128.33  4779.6  130.04
    4956   129.1  4989.4  118.71  5000.5  117.23  5006.5  117.72  5044.4  128.86
  5209.8   129.7  5279.7  129.53  5369.7  129.03  5389.7  126.73  5419.7  125.73
  5449.7  129.33  5599.7  129.43  5639.7  127.63  5709.7  129.03  5729.7  128.63
  5749.7  127.33  5799.7  126.93  5829.7  128.93  5899.7  130.43  6249.7  130.43
#Mann= 6 ,-1 , 0
  3191.4     .09       0  4500.5     .06       0    4956     .04       0
  5044.4     .06       0  5209.8      .1       0  5279.7     .99       0
Levee=-1,4781.08,129.95,-1,5598.58,129.36,,
#XS Ineff= 2 , 0
       0 4963.94     129 5035.65       0     129
Permanent Ineff=
       F       F
Bank Sta=4956,5044.4
XS Rating Curve= 0
Exp/Cntr=.5,.3

Type RM Length L Ch R = 1 ,7463.   ,797.6,798,791.2
BEGIN DESCRIPTION:
S8_FM2920 - XS 1
LIDAR overbanks, Interpolated channel
END DESCRIPTION:
XS GIS Cut Line= 5
      3087463.93     13953731.77       3086808.2     13953666.19
      3085719.32     13953552.39      3085616.58     13953549.54
       3084633.1     13954265.94
#Sta/Elev= 30
  3191.9  130.63  3311.9   129.1  3471.9  130.44  3541.9  128.75  3701.9   130.9
  3741.9  129.82  4060.9  129.66  4390.9  129.64  4740.9  127.74  4945.7  129.99
 4971.16  126.37 4993.68  118.11 5000.93  116.81 5034.97  126.39 5058.79  128.63
  5168.5  129.04  5198.5  127.96  5238.5  129.12  5338.5  128.46  5378.5  126.55
  5408.5  129.09  5478.5  129.97  5698.5  128.47  5708.5  128.16  5728.5  124.41
  5808.5  130.08  6038.5  129.84  6088.5   127.7  6168.5  129.93  6265.2  129.85
#Mann= 6 ,-1 , 0
  3191.9     .06       0  4060.9      .1       0  4945.7     .04       0
 5058.79     .07       0  5238.5     .06       0  5338.5     .99       0
Levee=-1,4830.9,129.5,-1,5538.5,130.08,,
#XS Ineff= 2 , 0
       0                 5132.65       0     129
Permanent Ineff=
       F       F
Bank Sta=4945.7,5058.79
XS Rating Curve= 0
Exp/Cntr=.3,.1

Type RM Length L Ch R = 1 ,6665    ,86.2,94,104.3
BEGIN DESCRIPTION:
S07_PL - XS 4
LIDAR overbanks, Interpolated channel
END DESCRIPTION:
XS GIS Cut Line= 6
 3087117.946580413953008.0390947 3085768.9382537 13952769.739642
 3085747.178472613952766.0981881 3085690.259189613952754.4601472
 3085648.254363513952748.9632019 3084944.499201613953320.4211399
#Sta/Elev= 30
  3576.6  129.62  3666.6  130.57  3956.6  130.19  4006.6   128.4  4046.6  130.52
  4146.6  130.47  4426.6  128.65  4486.6  126.79  4536.6  128.18  4616.6  128.68
  4876.6   128.7 4930.13   128.4 4971.16  126.37 4993.68  118.11 5000.93  116.81
 5034.97  126.39 5055.75  127.68 5058.79  128.63  5096.4  129.72  5176.4  129.99
  5346.4  128.82  5366.4  129.39  5456.4  126.88  5576.4  128.73  5636.4  128.91
  5696.4  127.45  5736.4  127.66  5756.4  128.74  5876.4  126.96  5916.5  128.46
#Mann= 5 ,-1 , 0
  3576.6     .99       0  4876.6     .06       0 4930.13     .04       0
 5058.79      .1       0  5176.4     .99       0
Levee=-1,4876.6,128.7,-1,5176.4,129.99,,
Bank Sta=4930.13,5058.79
XS Rating Curve= 0
Exp/Cntr=.5,.3

Type RM Length L Ch R = 1 ,6571    ,50.7,51,55.3
BEGIN DESCRIPTION:
S07_PL - XS 3
END DESCRIPTION:
XS GIS Cut Line= 4
 3087081.845451913952921.8295998      3085753.31      13952673.4
       3085656.6      13952651.2 3084977.4417886  13953210.91731
#Sta/Elev= 30
  3589.6  130.51  3929.6  129.54  4049.6  130.29  4149.6  129.57  4219.6  127.78
  4469.6  127.07  4629.6  128.58  4689.6   128.2  4719.6  128.84  4749.6  127.79
  4759.6  126.74  4779.6  126.23  4809.6  128.29    4868  128.69 4915.48  129.08
 4969.78  126.99 4993.38  118.17 4997.78   116.9 5000.98  116.77 5035.88  126.68
 5057.18  127.63  5060.3  128.61  5210.4  129.62  5240.4  128.63  5470.4  129.44
  5590.4  128.34  5640.4   126.6  5720.4  127.05  5760.4  128.99  5920.4  129.37
#Mann= 5 ,-1 , 0
  3589.6     .99       0    4868      .1       0 4915.48     .04       0
  5060.3      .1       0  5210.4     .99       0
Levee=-1,4900.98,128.28,-1,5198.49,128.39,,
#XS Ineff= 2 , 0
       0 4980.45  123.08  5024.2       0  123.22
Permanent Ineff=
       F       F
Bank Sta=4915.48,5060.3
XS Rating Curve= 0
Exp/Cntr=.5,.3

Type RM Length L Ch R = 3 ,6561    ,,,
BEGIN DESCRIPTION:
PL1_K124-02-00-S07 contours show detention pond-taken out 10/25/02 VRR
Pipeline crossing 1000' DS FM 2920
END DESCRIPTION:
Bridge Culvert--1,0,-1,-1, 0
Deck Dist Width WeirC Skew NumUp NumDn MinLoCord MaxHiCord MaxSubmerge Is_Ogee
10,3,2.6,0, 53, 53, , , .95, 0, ,,,
  3589.6  3929.6  4049.6  4149.6  4219.6  4279.6  4469.6  4629.6  4689.6  4719.6
  4729.6  4749.6  4759.6  4779.6  4809.6    4868  4869.6 4915.48 4945.18 4969.78
 4978.78 4980.58 4981.28 4988.21  4988.3 4993.38 4996.88 4997.78 5000.98 5002.38
 5003.18 5008.58 5013.22 5013.33 5020.48 5023.98 5035.88 5041.08 5057.18  5060.3
  5060.4  5068.3  5100.4  5120.4  5210.4  5240.4  5460.4  5470.4  5590.4  5640.4
  5720.4  5760.4  5920.4
   130.5  129.53  130.28  129.56  127.77  127.91  127.06  128.57  128.19  128.83
  128.75  127.78  126.73  126.22  128.28  128.68  128.69  129.07  127.64  126.98
  123.77  123.08  123.08   123.1   123.1  123.11  123.12  123.12  123.13  123.13
  123.14  123.15  123.16  123.16  123.18  123.19  126.67  127.04  127.62   128.6
  128.63  128.67  128.84  128.68  129.61  128.62  129.39  129.43  128.33  126.59
  127.04  128.98  129.36
   130.5  129.53  130.28  129.56  127.77  127.91  127.06  128.57  128.19  128.83
  128.75  127.78  126.73  126.22  128.28  128.68  128.69  129.07  127.64  126.98
  123.77  123.08  122.81  120.15  120.11  120.11  120.12  120.12  120.13  120.13
  120.14  120.15  120.16  120.16  122.09  123.13  126.67  127.04  127.62   128.6
  128.63  128.67  128.84  128.68  129.61  128.62  129.39  129.43  128.33  126.59
  127.04  128.98  129.36
  3589.6  3929.6  4049.6  4149.6  4219.6  4279.6  4469.6  4629.6  4689.6  4719.6
  4729.6  4749.6  4759.6  4779.6  4809.6    4868  4869.6 4915.48 4945.18 4969.78
 4978.78 4980.58 4981.28 4988.21  4988.3 4993.38 4996.88 4997.78 5000.98 5002.38
 5003.18 5008.58 5013.22 5013.33 5020.48 5023.98 5035.88 5041.08 5057.18  5060.3
  5060.4  5068.3  5100.4  5120.4  5210.4  5240.4  5460.4  5470.4  5590.4  5640.4
  5720.4  5760.4  5920.4
   130.5  129.53  130.28  129.56  127.77  127.91  127.06  128.57  128.19  128.83
  128.75  127.78  126.73  126.22  128.28  128.68  128.69  129.07  127.64  126.98
  123.77  123.08  123.08   123.1   123.1  123.11  123.12  123.12  123.13  123.13
  123.14  123.15  123.16  123.16  123.18  123.19  126.67  127.04  127.62   128.6
  128.63  128.67  128.84  128.68  129.61  128.62  129.39  129.43  128.33  126.59
  127.04  128.98  129.36
   130.5  129.53  130.28  129.56  127.77  127.91  127.06  128.57  128.19  128.83
  128.75  127.78  126.73  126.22  128.28  128.68  128.69  129.07  127.64  126.98
  123.77  123.08  122.81  120.15  120.11  120.11  120.12  120.12  120.13  120.13
  120.14  120.15  120.16  120.16  122.09  123.13  126.67  127.04  127.62   128.6
  128.63  128.67  128.84  128.68  129.61  128.62  129.39  129.43  128.33  126.59
  127.04  128.98  129.36
BR Coef= 1 , 1 , 0 ,1.25, 0 ,,,.8,0,2,0,
WSPro=,,,, 1 ,,,, 0 ,,,, 0 ,,,,-1 ,-1 ,-1 , 0 , 0 , 0 , 0 , 0
BR U #Sta/Elev= 53
  3589.6   130.5  3929.6  129.53  4049.6  130.28  4149.6  129.56  4219.6  127.77
  4279.6  127.91  4469.6  127.06  4629.6  128.57  4689.6  128.19  4719.6  128.83
  4729.6  128.75  4749.6  127.78  4759.6  126.73  4779.6  126.22  4809.6  128.28
    4868  128.68  4869.6  128.69 4915.48  129.07 4945.18  127.64 4969.78  126.98
 4978.78  123.77 4980.58  123.08 4981.28  122.81 4988.21  120.15  4988.3  120.11
 4993.38  118.16 4996.88   117.3 4997.78  116.89 5000.98  116.76 5002.38  116.87
 5003.18  117.38 5008.58  118.87 5013.22  120.13 5013.33  120.16 5020.48  122.09
 5023.98  123.13 5035.88  126.67 5041.08  127.04 5057.18  127.62  5060.3   128.6
  5060.4  128.63  5068.3  128.67  5100.4  128.84  5120.4  128.68  5210.4  129.61
  5240.4  128.62  5460.4  129.39  5470.4  129.43  5590.4  128.33  5640.4  126.59
  5720.4  127.04  5760.4  128.98  5920.4  129.36
BR U #Mann= 5
  3589.6     .99    4868      .1 4915.48     .04  5060.3      .1  5210.4     .99
BR U Banks=4915.48,5060.3
BR D #Sta/Elev= 53
  3589.6   130.5  3929.6  129.53  4049.6  130.28  4149.6  129.56  4219.6  127.77
  4279.6  127.91  4469.6  127.06  4629.6  128.57  4689.6  128.19  4719.6  128.83
  4729.6  128.75  4749.6  127.78  4759.6  126.73  4779.6  126.22  4809.6  128.28
    4868  128.68  4869.6  128.69 4915.48  129.07 4945.18  127.64 4969.78  126.98
 4978.78  123.77 4980.58  123.08 4981.28  122.81 4988.21  120.15  4988.3  120.11
 4993.38  118.16 4996.88   117.3 4997.78  116.89 5000.98  116.76 5002.38  116.87
 5003.18  117.38 5008.58  118.87 5013.22  120.13 5013.33  120.16 5020.48  122.09
 5023.98  123.13 5035.88  126.67 5041.08  127.04 5057.18  127.62  5060.3   128.6
  5060.4  128.63  5068.3  128.67  5100.4  128.84  5120.4  128.68  5210.4  129.61
  5240.4  128.62  5460.4  129.39  5470.4  129.43  5590.4  128.33  5640.4  126.59
  5720.4  127.04  5760.4  128.98  5920.4  129.36
BR D #Mann= 5
  3589.6     .99    4868      .1 4915.48     .04  5060.3      .1  5210.4     .99
BR D Banks=4915.48,5060.3
BC Design=,, 0 ,, 0 ,,,,,,
BC HTab HWMax=130.51

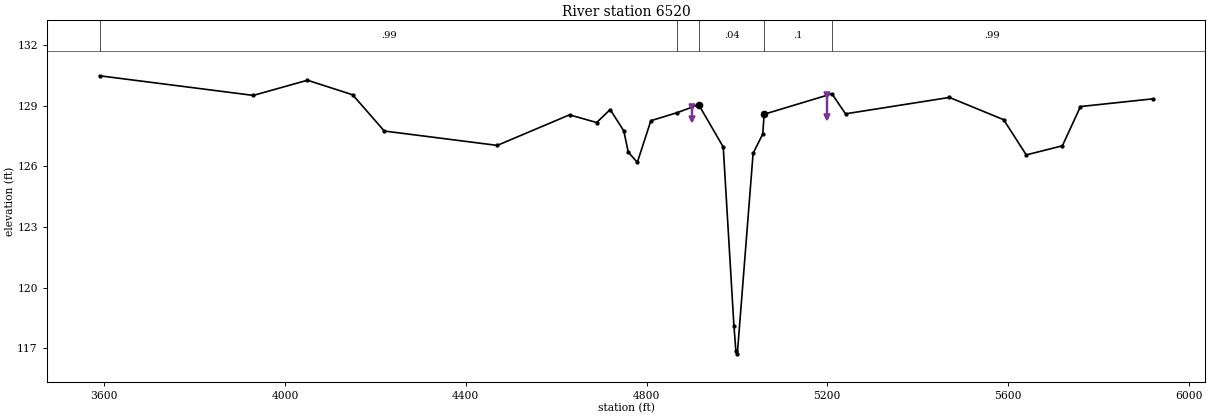
Type RM Length L Ch R = 1 ,6520    ,113.2,105,94.7
BEGIN DESCRIPTION:
S07_PL - XS 2
END DESCRIPTION:
XS GIS Cut Line= 4
 3087083.274139713952871.2287113      3085758.67     13952623.51
      3085652.77     13952599.28 3084977.877077213953155.4577368
#Sta/Elev= 30
  3589.6  130.47  3929.6   129.5  4049.6  130.25  4149.6  129.53  4219.6  127.74
  4469.6  127.03  4629.6  128.54  4689.6  128.16  4719.6   128.8  4749.6  127.75
  4759.6   126.7  4779.6  126.19  4809.6  128.25    4868  128.65 4915.48  129.04
 4969.78  126.95 4993.38  118.13 4997.78  116.86 5000.98  116.73 5035.88  126.64
 5057.18  127.59  5060.3  128.57  5210.4  129.58  5240.4  128.59  5470.4   129.4
  5590.4   128.3  5640.4  126.56  5720.4  127.01  5760.4  128.95  5920.4  129.33
#Mann= 5 ,-1 , 0
  3589.6     .99       0    4868      .1       0 4915.48     .04       0
  5060.3      .1       0  5210.4     .99       0
Levee=-1,4900.98,128.34,-1,5198.49,128.44,,
#XS Ineff= 2 , 0
       0 4980.45   121.5  5024.2       0   121.5
Permanent Ineff=
       F       F
Bank Sta=4915.48,5060.3
XS Rating Curve= 0
Exp/Cntr=.5,.3