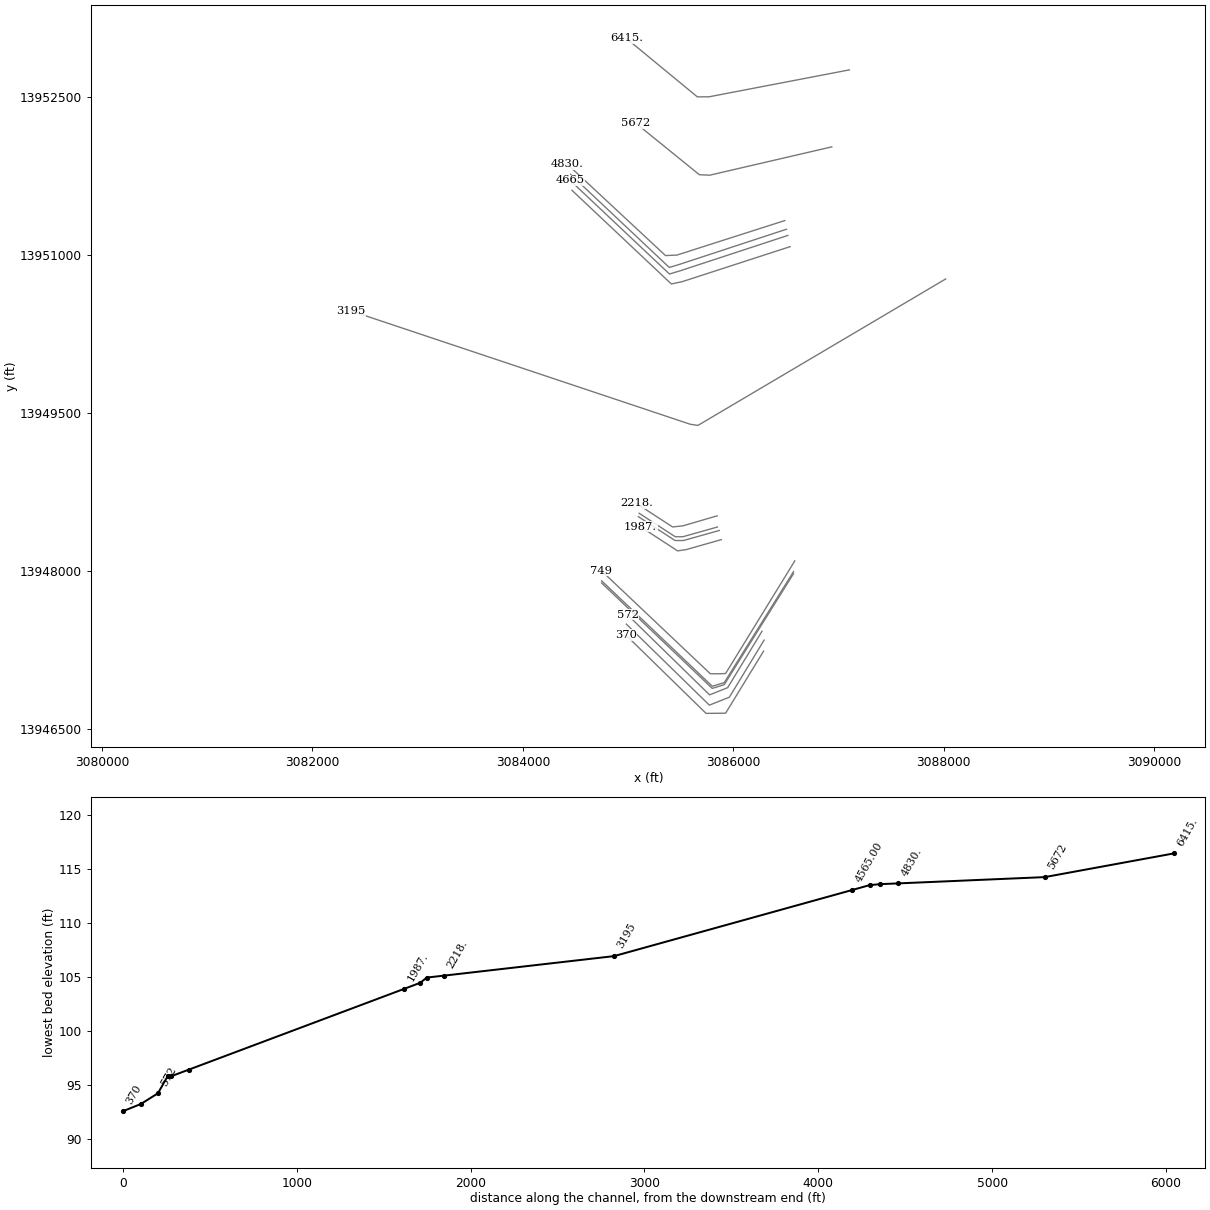
HEC-RAS study K124-02-00.prj: K124-02-00

--- K124-02-00.g01 (geometry) --- (continued)

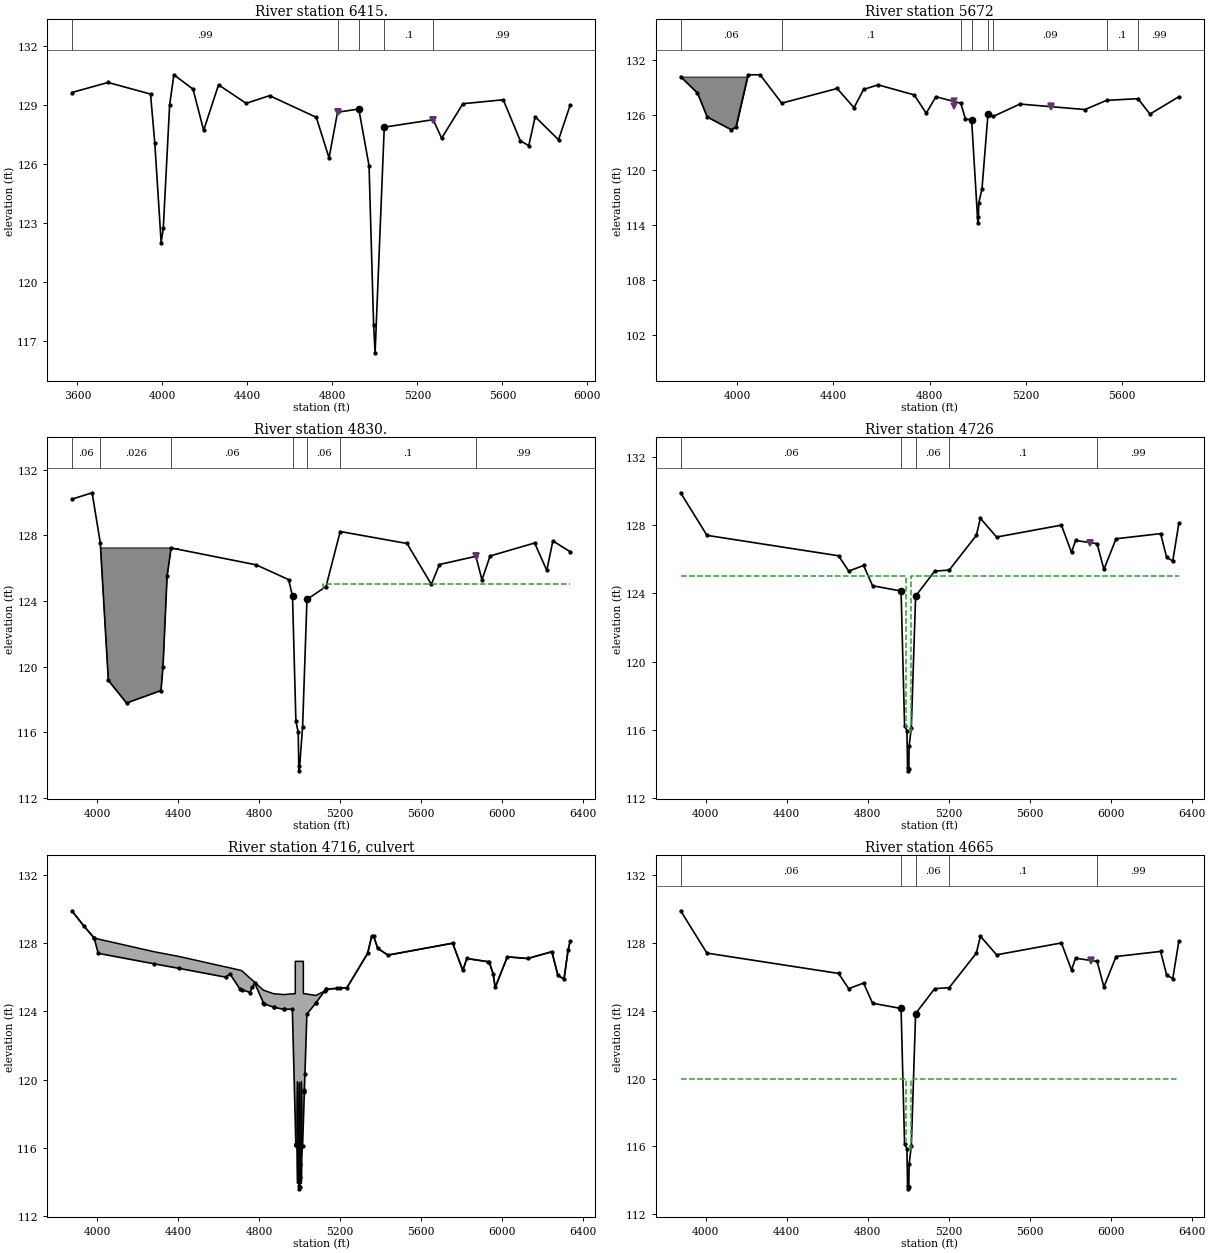
Type RM Length L Ch R = 1 ,6415.   ,745.1,743,741
BEGIN DESCRIPTION:
S07_PL - XS 1
LIDAR overbanks, Interpolated channel
END DESCRIPTION:
XS GIS Cut Line= 4
      3087102.83     13952760.88      3085768.75     13952505.02
      3085657.28     13952504.44      3084982.39     13953060.62
#Sta/Elev= 30
  3574.1  129.64  3744.1  130.15  3944.1  129.56  3964.1  127.09  3994.1  122.02
  4004.1  122.74  4034.1  129.02  4054.1  130.54  4144.1  129.81  4194.1  127.72
  4264.1  130.03  4394.1  129.09  4504.1  129.48  4724.1  128.38  4784.1  126.32
  4824.1  128.64  4924.1   128.8 4972.36  125.92 4993.92  117.81 5000.86  116.42
    5044  127.88    5274  128.26    5314  127.32    5414  129.07    5604  129.27
    5684  127.19    5724  126.94    5754  128.41    5864  127.24  5918.5  128.99
#Mann= 5 ,-1 , 0
  3574.1     .99       0  4824.1      .1       0  4924.1     .04       0
    5044      .1       0    5274     .99       0
Levee=-1,4824.1,128.64,-1,5274,128.26,,
Bank Sta=4924.1,5044
XS Rating Curve= 0
Exp/Cntr=.3,.1

Type RM Length L Ch R = 1 ,5672    ,833.4,842,845.2
BEGIN DESCRIPTION:
Cross Section K124-02-00-X02
Contours show excavated area which are blocked out 10/25/02 VRR
END DESCRIPTION:
XS GIS Cut Line= 4
 3086935.276063813952029.2297059       3085775.7     13951760.15
      3085677.18     13951764.26 3085071.197426513952255.3849638
#Sta/Elev= 30
  3765.8   130.2  3835.8   128.4  3875.8   125.8  3975.8   124.4  3995.8   124.7
  4045.8   130.4  4095.8   130.4  4185.8   127.3  4415.8   128.9  4485.8   126.8
  4525.8   128.8  4585.8   129.3  4735.8   128.2  4785.8   126.2  4825.8     128
    4929  127.29  4948.7  125.57  4974.3  125.46    5000  114.23  5002.6  114.86
  5003.7  116.38  5017.2  117.89  5042.1  126.08  5065.1  125.86  5174.8   127.2
  5444.8   126.6  5534.8   127.6    5665  127.79  5714.8   126.1  5834.8     128
#Mann= 8 ,-1 , 0
  3765.8     .06       0  4185.8      .1       0    4929    .045       0
  4974.3     .04       0  5042.1    .045       0  5065.1     .09       0
  5534.8      .1       0    5665     .99       0
Levee=-1,4900.98,126.97,-1,5302.84,126.97,,
#Block Obstruct= 2 ,-1
 3765.27 4045.22   130.2 4046.22 4047.22     100
Bank Sta=4974.3,5042.1
XS Rating Curve= 0
Exp/Cntr=.3,.1

Type RM Length L Ch R = 1 ,4830.   ,92,104,94.5
BEGIN DESCRIPTION:
S3A_SPRING CYPRESS-DS - XS 4
LIDAR overbanks, Interpolated channel
END DESCRIPTION:
XS GIS Cut Line= 4
      3086488.56     13951328.72      3085462.65     13951000.58
      3085355.05     13950995.97      3084421.76     13951864.93
#Sta/Elev= 30
  3876.6   130.2  3976.6  130.59  4016.6  127.55  4056.6  119.16  4146.6  117.78
  4316.6  118.54  4326.6     120  4346.6  125.49  4366.6  127.23  4786.6   126.2
  4946.6   125.3 4965.93  124.29 4982.65  116.66 4994.02  116.01 4996.94  113.93
 4999.47  113.65 5015.79  116.35 5037.29  124.09  5131.4  124.88  5201.4  128.23
  5531.4   127.5  5651.4  125.01  5691.4  126.22  5871.4  126.72  5901.4  125.28
  5941.4  126.74  6161.4  127.53  6221.4  125.86  6251.4  127.66  6336.6     127
#Mann= 7 ,-1 , 0
  3876.6     .06       0  4016.6    .026       0  4366.6     .06       0
 4965.93     .04       0 5037.29     .06       0  5201.4      .1       0
  5871.4     .99       0
Levee=0,,,-1,5871.4,126.72,,
#XS Ineff= 2 , 0
       0  4883.3  125.05  5116.5       0  125.05
Permanent Ineff=
       F       F
#Block Obstruct= 2 , 0
       0    4400  127.23               0
Bank Sta=4965.93,5037.29
XS Rating Curve= 0
Exp/Cntr=.5,.3

Type RM Length L Ch R = 1 ,4726    ,60.3,61,72.7
BEGIN DESCRIPTION:
U S3A_SPRING CYPRESS-DS - XS 3
END DESCRIPTION:
XS GIS Cut Line= 4
 3086503.925134713951246.1299004      3085479.69     13950909.75
      3085391.07     13950883.07 3084452.522523313951767.6619826
#Sta/Elev= 30
  3876.2  129.91  4006.2  127.41  4656.2  126.21  4706.2  125.31  4779.7  125.64
  4824.2  124.45  4964.9  124.14  4982.1  116.24  4993.8  115.94  4996.8  113.76
  4999.4  113.58    5003  113.69  5004.8  115.05  5015.5  116.12  5036.7  123.84
  5130.8  125.31  5202.6  125.37  5336.6  127.41  5356.6  128.41  5436.6  127.31
  5756.6  128.01  5806.6  126.41  5826.6  127.11    5933  126.92  5966.6  125.41
  6026.6  127.21  6246.6  127.51  6276.6  126.11  6306.6  125.91  6336.6  128.11
#Mann= 5 ,-1 , 0
  3876.2     .06       0  4964.9     .04       0  5036.7     .06       0
  5202.6      .1       0    5933     .99       0
Levee=0,,,-1,5897.94,126.98,,
#XS Ineff= 2 , 0
       0  4987.3  125.05  5012.5       0  125.05
Permanent Ineff=
       F       F
Bank Sta=4964.9,5036.7
XS Rating Curve= 0
Exp/Cntr=.5,.3

Type RM Length L Ch R = 2 ,4716    ,,,
BEGIN DESCRIPTION:
SPRING CYPRESS
Structure ID: K124-02-00-S3A
Picture shows two end culverts as half blocked out
END DESCRIPTION:
Bridge Culvert--1,0,-1,-1, 0
Deck Dist Width WeirC Skew NumUp NumDn MinLoCord MaxHiCord MaxSubmerge Is_Ogee
10,41,2.6,0, 66, 66, , , .95, 0, ,,,
  3876.2  3936.2  3984.1  3986.2  4006.2  4284.1  4404.1  4636.2  4656.2  4706.2
  4714.1  4756.2  4766.2  4779.7  4822.2  4824.2    4872  4873.2  4921.3  4922.1
  4964.9  4977.1  4977.2 4979.39  4979.5 4979.61  4988.8  4991.4  4991.8  4994.4
    4998  4998.5  4999.8  5010.5 5019.19  5019.3 5019.41  5027.1  5036.7  5079.4
  5081.6  5123.8  5130.8  5131.5  5183.3  5202.6  5234.2  5336.6  5356.6  5366.6
  5386.6  5436.6  5756.6  5806.6  5826.6    5933  5936.6  5956.6  5966.6  6026.6
  6126.6  6246.6  6276.6  6306.6  6326.6  6336.6
   129.9     129  128.34   128.3  128.25   127.5  127.23  126.61  126.56  126.42
   126.4  125.95  125.85   125.7  125.25  125.24  125.04  125.04  124.99  124.99
  125.03  125.04  125.04  125.04  126.94  126.94  126.94  126.94  126.94  126.94
  126.94  126.94  126.94  126.94  126.94  126.94  125.04  125.04  125.02  124.94
  124.94  125.19  125.31  125.31  125.35  125.37  125.38   127.4   128.4   128.4
   127.7   127.3     128   126.4   127.1  126.91   126.9   126.2   125.4   127.2
   127.1   127.5   126.1   125.9   127.6   128.1
                                                                                
                                                                                
                                                                                
                                                                                
                                                                                
                                                                                
                                                
  3876.2  3936.2  3984.1  3986.2  4006.2  4284.1  4404.1  4636.2  4656.2  4706.2
  4714.1  4756.2  4766.2  4779.7  4822.2  4824.2    4872  4873.2  4921.3  4922.1
  4964.9  4977.1  4977.2 4979.39  4979.5 4979.61  4988.8  4991.4  4991.8  4994.4
    4998  4998.5  4999.8  5010.5 5019.19  5019.3 5019.41  5027.1  5036.7  5079.4
  5081.6  5123.8  5130.8  5131.5  5183.3  5202.6  5234.2  5336.6  5356.6  5366.6
  5386.6  5436.6  5756.6  5806.6  5826.6    5933  5936.6  5956.6  5966.6  6026.6
  6126.6  6246.6  6276.6  6306.6  6326.6  6336.6
   129.9     129  128.34   128.3  128.25   127.5  127.23  126.61  126.56  126.42
   126.4  125.95  125.85   125.7  125.25  125.24  125.04  125.04  124.99  124.99
  125.03  125.04  125.04  125.04  126.94  126.94  126.94  126.94  126.94  126.94
  126.94  126.94  126.94  126.94  126.94  126.94  125.04  125.04  125.02  124.94
  124.94  125.19  125.31  125.31  125.35  125.37  125.38   127.4   128.4   128.4
   127.7   127.3     128   126.4   127.1  126.91   126.9   126.2   125.4   127.2
   127.1   127.5   126.1   125.9   127.6   128.1
                                                                                
                                                                                
                                                                                
                                                                                
                                                                                
                                                                                
                                                
BR Coef= 1 , 1 , 1 ,1.25, 0 ,,,.8,0,2,0,
WSPro=,,,, 1 ,,,, 0 ,,,, 0 ,,,,-1 ,-1 ,-1 , 0 , 0 , 0 , 0 , 0
Culvert=1,6,,57,.024,.4,1,2,1,113.89,4990.3,112.89,4990.3,Culvert #1  , 0 ,3
Culvert Bottom n=.024
Culvert=1,6,,57,.024,.4,1,2,1,113.82,4999.7,112.92,4999.7,Culvert #2  , 0 ,3
Culvert Bottom n=.024
Culvert=1,6,,57,.024,.4,1,2,1,113.89,5009.5,112.93,5009.5,Culvert #3  , 0 ,3
Culvert Bottom n=.024
BR U #Sta/Elev= 66
  3876.2  129.91  3936.2  129.01  3984.1  128.34  3986.2  128.31  4006.2  127.41
  4284.1  126.79  4404.1  126.53  4636.2  126.01  4656.2  126.21  4706.2  125.31
  4714.1  125.28  4756.2  125.11  4766.2  125.41  4779.7  125.64  4822.2   124.5
  4824.2  124.45    4872  124.25  4873.2  124.25  4921.3  124.12  4922.1  124.12
  4964.9  124.14  4982.1  116.24  4982.2  116.24 4984.39  116.18  4984.5  116.18
 4984.61  116.18  4993.8  115.94  4996.4  114.35  4996.8  113.76  4999.4  113.58
    5003  113.69  5003.5   114.3  5004.8  115.05  5015.5  116.12 5024.19  119.28
  5024.3  119.32 5024.41  119.36  5027.1  120.34  5036.7  123.84  5079.4  124.47
  5081.6   124.5  5123.8  125.19  5130.8  125.31  5131.5  125.31  5183.3  125.35
  5202.6  125.37  5234.2  125.39  5336.6  127.41  5356.6  128.41  5366.6  128.41
  5386.6  127.71  5436.6  127.31  5756.6  128.01  5806.6  126.41  5826.6  127.11
    5933  126.92  5936.6  126.91  5956.6  126.21  5966.6  125.41  6026.6  127.21
  6126.6  127.11  6246.6  127.51  6276.6  126.11  6306.6  125.91  6326.6  127.61
  6336.6  128.11
BR U #Mann= 5
  3876.2     .06  4964.9     .04  5036.7     .06  5202.6      .1    5933     .99
BR D #Sta/Elev= 66
  3876.2  129.91  3936.2  129.01  3984.1  128.34  3986.2  128.31  4006.2  127.41
  4284.1  126.79  4404.1  126.53  4636.2  126.01  4656.2  126.21  4706.2  125.31
  4714.1  125.28  4756.2  125.11  4766.2  125.41  4779.7  125.64  4822.2   124.5
  4824.2  124.45    4872  124.25  4873.2  124.25  4921.3  124.12  4922.1  124.12
  4964.9  124.14  4982.1  116.15  4982.2  116.15 4984.39  116.09  4984.5  116.09
 4984.61  116.09  4993.8  115.85  4996.4  114.26  4996.8  113.67  4999.4  113.49
    5003   113.6  5003.5  114.21  5004.8  114.96  5015.5  116.03 5024.19  119.19
  5024.3  119.23 5024.41  119.27  5027.1  120.25  5036.7  123.84  5079.4  124.47
  5081.6   124.5  5123.8  125.19  5130.8  125.31  5131.5  125.31  5183.3  125.35
  5202.6  125.37  5234.2  125.39  5336.6  127.41  5356.6  128.41  5366.6  128.41
  5386.6  127.71  5436.6  127.31  5756.6  128.01  5806.6  126.41  5826.6  127.11
    5933  126.92  5936.6  126.91  5956.6  126.21  5966.6  125.41  6026.6  127.21
  6126.6  127.11  6246.6  127.51  6276.6  126.11  6306.6  125.91  6326.6  127.61
  6336.6  128.11
BR D #Mann= 5
  3876.2     .06  4964.9     .04  5036.7     .06  5202.6      .1    5933     .99
BC Design=,, 0 ,, 0 ,,,,,,
BC HTab HWMax=129.91

Type RM Length L Ch R = 1 ,4665    ,104.9,100,93.5
BEGIN DESCRIPTION:
S3A_SPRING CYPRESS-DS - XS 2
END DESCRIPTION:
XS GIS Cut Line= 4
 3086517.148833513951187.3490869      3085492.68      13950850.9
      3085392.75     13950820.82 3084445.783929813951713.3528649
#Sta/Elev= 30
  3876.2  129.91  4006.2  127.41  4656.2  126.21  4706.2  125.31  4779.7  125.64
  4824.2  124.45  4964.9  124.14  4982.1  116.15  4993.8  115.85  4996.8  113.67
  4999.4  113.49    5003   113.6  5004.8  114.96  5015.5  116.03  5036.7  123.84
  5130.8  125.31  5202.6  125.37  5336.6  127.41  5356.6  128.41  5436.6  127.31
  5756.6  128.01  5806.6  126.41  5826.6  127.11    5933  126.92  5966.6  125.41
  6026.6  127.21  6246.6  127.51  6276.6  126.11  6306.6  125.91  6336.6  128.11
#Mann= 5 ,-1 , 0
  3876.2     .06       0  4964.9     .04       0  5036.7     .06       0
  5202.6      .1       0    5933     .99       0
Levee=0,,,-1,5904.12,126.98,,
#XS Ineff= 2 , 0
       0  4987.3     120  5012.5       0     120
Permanent Ineff=
       F       F
Bank Sta=4964.9,5036.7
XS Rating Curve= 0
Exp/Cntr=.5,.3

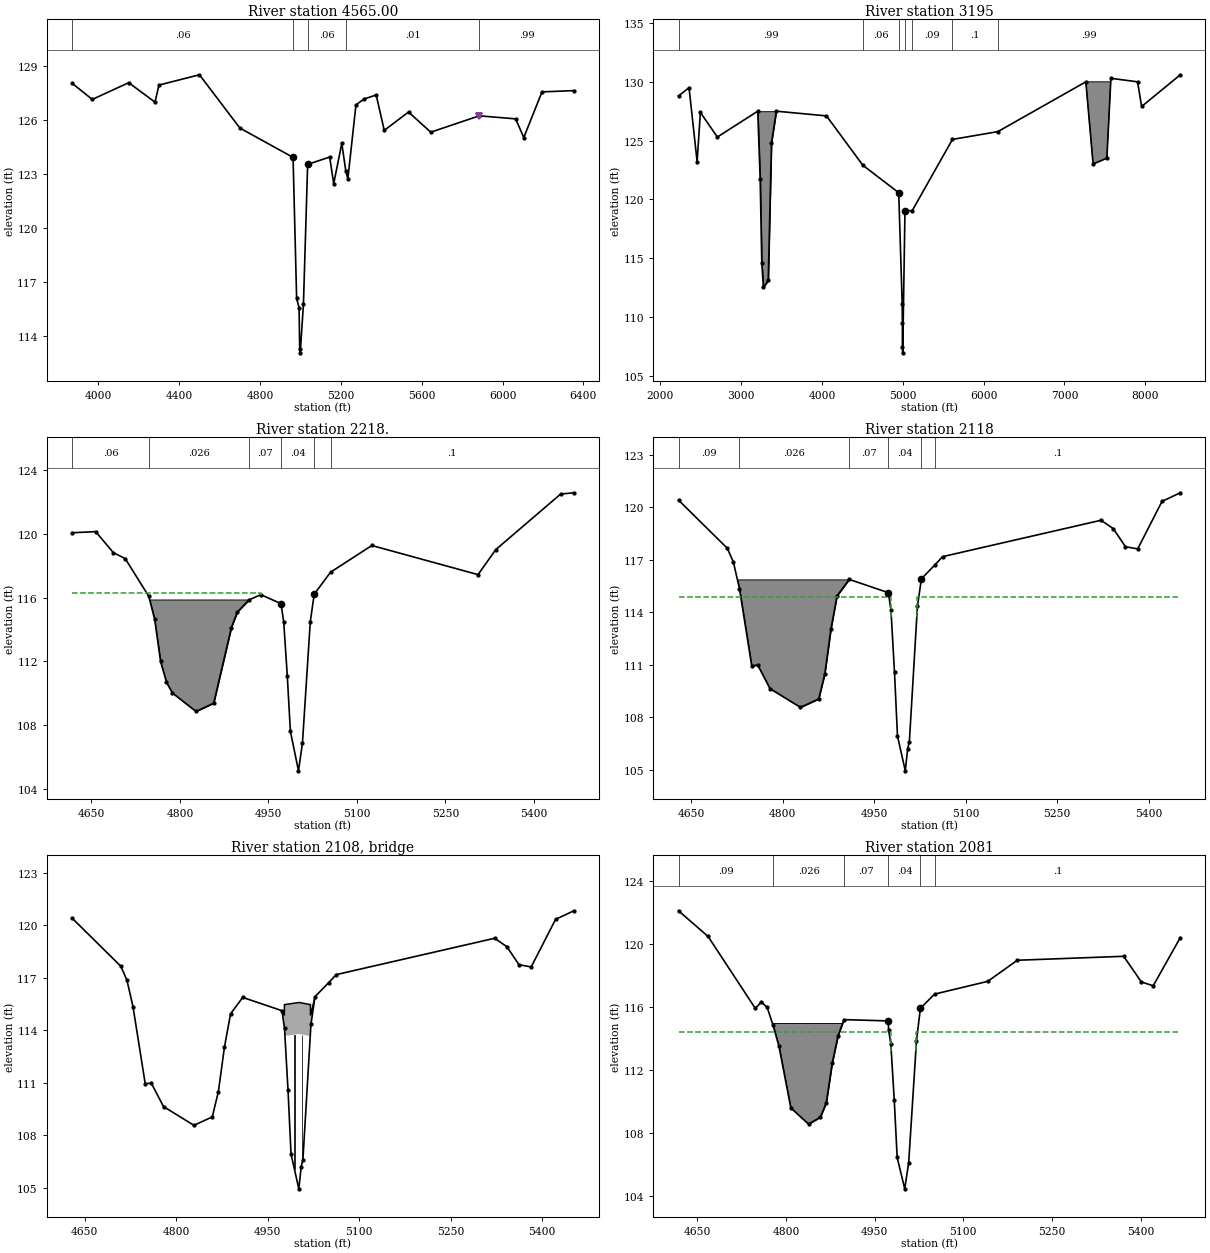
Type RM Length L Ch R = 1 ,4565.00 ,1384.5,1370,1373.7
BEGIN DESCRIPTION:
S3A_SPRING CYPRESS-DS - XS 1
LIDAR overbanks, Interpolated channel
END DESCRIPTION:
XS GIS Cut Line= 4
      3086539.47     13951080.98      3085514.92     13950748.48
      3085410.39     13950726.19      3084466.11     13951616.26
#Sta/Elev= 30
    3871  128.02    3971  127.12    4151  128.05    4281  126.97    4301  127.92
    4501  128.49    4701  125.53 4963.93   123.9 4981.64  116.06 4993.68  115.54
 4996.77  113.24 4999.45  113.04 5015.27  115.74  5036.1  123.51    5145  123.92
    5165  122.44    5205  124.68    5225  123.13    5235  122.71    5275  126.82
    5315  127.14    5375  127.37    5415   125.4    5535  126.42    5645   125.3
    5885  126.21    6065  126.04    6105     125    6195  127.54  6352.7  127.61
#Mann= 5 ,-1 , 0
    3871     .06       0 4963.93     .04       0  5036.1     .06       0
    5225     .01       0    5885     .99       0
Levee=0,,,-1,5885,126.21,,
Bank Sta=4963.93,5036.1
XS Rating Curve= 0
Exp/Cntr=.3,.1

Type RM Length L Ch R = 1 ,3195    ,966,977,990.5
BEGIN DESCRIPTION:
Cross Section K124-02-00-X01
END DESCRIPTION:
XS GIS Cut Line= 4
      3088017.47     13950773.73       3085663.5     13949382.24
      3085590.12     13949393.07      3082366.43     13950469.91
#Sta/Elev= 30
  2226.7   128.8  2356.7   129.5  2456.7   123.2  2496.7   127.4  2706.7   125.3
  3206.7   127.5  3236.7   121.7  3256.7   114.6  3276.7   112.5  3336.7   113.1
  3376.7   124.8  3436.7   127.5  4056.7   127.1  4506.7   122.9  4950.6  120.56
  4993.6  111.07    4996  109.49  4996.2  107.41  5000.1  106.93  5027.9  119.03
  5117.1  119.03  5615.4   125.1  6176.7  125.76  7265.4     130  7355.4     123
  7525.4   123.5  7575.4   130.3  7905.4     130  7955.4   127.9  8434.2   130.6
#Mann= 7 ,-1 , 0
  2226.7     .99       0  4506.7     .06       0  4950.6     .04       0
  5027.9     .06       0  5117.1     .09       0  5615.4      .1       0
  6176.7     .99       0
#Block Obstruct= 2 ,-1
 3206.84 3435.69   127.5 7265.07 7575.03     130
Bank Sta=4950.6,5027.9
XS Rating Curve= 0
Exp/Cntr=.3,.1

Type RM Length L Ch R = 1 ,2218.   ,100.4,100,95
BEGIN DESCRIPTION:
S02_WOOD BRIDGE - XS 4
LIDAR overbanks, Interpolated channel
END DESCRIPTION:
XS GIS Cut Line= 4
      3085845.93     13948522.65      3085520.41     13948427.53
      3085422.12     13948416.96      3085076.52     13948642.08
#Sta/Elev= 30
  4617.2  120.08  4657.2  120.15  4687.2  118.83  4707.2  118.46  4747.2  116.09
  4757.2  114.64  4767.2     112  4777.2  110.69  4787.2  110.02  4827.2  108.86
  4857.2  109.38  4887.2  114.13  4897.2   115.1  4917.2  115.87  4937.2  116.19
 4971.19  115.63 4971.51  115.56 4975.82   114.5 4981.92  111.11 4987.18  107.62
 5000.92  105.13 5007.65  106.88 5020.91  114.49 5027.54  116.22  5055.2   117.6
  5125.2  119.28  5305.2  117.45  5335.2  119.02  5445.2  122.51  5467.6  122.59
#Mann= 6 ,-1 , 0
  4617.2     .06       0  4747.2    .026       0  4917.2     .07       0
 4971.51     .04       0 5027.54    .045       0  5055.2      .1       0
#XS Ineff= 2 , 0
       0  4937.2   116.3               0
Permanent Ineff=
       F       F
#Block Obstruct= 2 , 0
       0    4950  115.89               0
Bank Sta=4971.19,5027.54
XS Rating Curve= 0
Exp/Cntr=.5,.3

Type RM Length L Ch R = 1 ,2118    ,36.5,37,38
BEGIN DESCRIPTION:
S02_WOOD BRIDGE - XS 3
END DESCRIPTION:
XS GIS Cut Line= 4
      3085848.36     13948416.37      3085519.14     13948323.86
      3085447.88     13948323.76      3085104.16     13948547.18
#Sta/Elev= 30
    4629  120.42    4709  117.67    4719  116.88    4729  115.35    4749  110.96
    4759  110.99    4779  109.65    4829  108.58    4859  109.06    4869   110.5
    4879  113.05    4889  114.95    4909  115.89  4973.3  115.13  4977.5  114.13
  4983.3  110.57  4988.2  106.94    5001  104.95  5004.9  106.22  5007.7  106.62
  5020.9  114.35  5027.5  115.93  5050.2  116.74  5062.2  117.19  5322.2  119.27
  5342.2  118.79  5362.2  117.76  5382.2  117.63  5422.2  120.35  5452.2  120.84
#Mann= 6 ,-1 , 0
    4629     .09       0    4729    .026       0    4909     .07       0
  4973.3     .04       0  5027.5    .045       0  5050.2      .1       0
#XS Ineff= 2 , 0
       0 4978.18   114.9 5019.83       0  114.88
Permanent Ineff=
       F       F
#Block Obstruct= 2 , 0
       0    4909  115.89               0
Bank Sta=4973.3,5027.5
XS Rating Curve= 0
Exp/Cntr=.5,.3

Type RM Length L Ch R = 3 ,2108    ,,,
BEGIN DESCRIPTION:
WOOD BRIDGE 1500' US LOUETTA
Structure ID: K124-02-00-S02
Excavated portion on left was filled in because can't put
blocked obstructions on structures 10/25/02 VRR
END DESCRIPTION:
Bridge Culvert--1,0,-1,-1, 0
Deck Dist Width WeirC Skew NumUp NumDn MinLoCord MaxHiCord MaxSubmerge Is_Ogee
10,14,2.6,0, 24, 24, , , .95, 0, ,,,
  4973.3  4973.6 4977.29  4977.4  4977.5 4977.61 4978.11 4978.18  4983.3  4988.2
  4993.4  4999.6    5001  5002.1  5004.9  5007.7  5010.7 5019.71 5019.82 5019.86
    5020 5020.11  5020.9  5027.5
  115.12  115.05  114.88  115.48  115.48  115.48  115.48  115.48  115.51  115.53
  115.56  115.59  115.59   115.6  115.58  115.56  115.54  115.48  115.48  115.48
  115.48  114.88  114.96  115.92
                                                          113.68  113.71  113.73
  113.76  113.79  113.79   113.8  113.78  113.76  113.74  113.68  113.68
                                
  4973.3  4973.6 4977.29  4977.4  4977.5 4977.61 4978.11 4978.18  4983.3  4988.2
  4993.4  4999.6    5001  5002.1  5004.9  5007.7  5010.7 5019.71 5019.82 5019.86
    5020 5020.11  5020.9  5027.5
  115.12  115.05  114.88  115.48  115.48  115.48  115.48  115.48  115.51  115.53
  115.56  115.59  115.59   115.6  115.58  115.56  115.54  115.48  115.48  115.48
  115.48  114.88  114.96  115.92
                                                          113.68  113.71  113.73
  113.76  113.79  113.79   113.8  113.78  113.76  113.74  113.68  113.68
                                
Pier Skew, UpSta & Num, DnSta & Num=  ,4993.6, 2 ,4993.6, 2 , 0 , 0 , 0 ,,
       1       1
  104.88  114.76
       1       1
  104.49  114.37
Pier Skew, UpSta & Num, DnSta & Num=  ,5006.4, 2 ,5006.4, 2 , 0 , 0 , 0 ,,
       1       1
  105.34  114.77
       1       1
  104.95  114.38
BR Coef= 1 , 1 , 1 ,1.25, 0 ,,,.8,0,2,0,
WSPro=,,,, 1 ,,,, 0 ,,,, 0 ,,,,-1 ,-1 ,-1 , 0 , 0 , 0 , 0 , 0
BR D #Sta/Elev= 62
  4618.2  122.12  4648.2  120.92  4658.2  120.85  4668.2  120.49  4688.2  119.29
  4698.2  118.47  4728.2  116.85  4738.2  116.64  4748.2  115.92  4758.2  116.33
  4768.2  115.99  4778.2  114.85  4788.2  113.51  4798.2  111.26  4808.2  109.61
  4818.2  108.95  4838.2  108.58  4848.2  108.63  4858.2  109.02  4868.2  109.93
  4878.2  112.43  4888.2   114.2  4898.2  115.21  4908.2  115.22  4918.2  114.98
  4959.1  115.12  4969.7  115.13  4973.3  115.13  4973.6  114.58 4977.29   113.7
  4977.4  113.67  4977.5  113.65 4977.61  113.58 4978.11  113.28  4978.2  113.22
  4983.3  110.09  4988.2  106.46  4993.4   105.5  4999.6  104.81    5001  104.47
  5002.1  104.83  5004.9  105.74  5007.7  106.14  5010.7  107.74 5019.71  113.15
 5019.89  113.26    5020  113.33 5020.11   113.4  5020.9  113.87  5027.5  115.93
  5041.6  116.28  5051.5  116.83  5141.5  117.64  5191.5  118.98  5231.5  118.82
  5371.5  119.23  5391.5   118.4  5401.5   117.6  5411.5  117.33  5421.5  117.36
  5431.5  117.81  5467.4  120.42
BR D #Mann= 6
  4618.2     .09  4778.2    .026  4898.2     .07  4973.3     .04  5027.5    .045
  5051.5      .1
BC Design=,, 0 ,, 0 ,,,,,,
BC HTab HWMax=120.62

Type RM Length L Ch R = 1 ,2081    ,90.6,94,99.6
BEGIN DESCRIPTION:
S02_WOOD BRIDGE - XS 2
END DESCRIPTION:
XS GIS Cut Line= 4
      3085865.86     13948383.65      3085525.67     13948288.06
      3085445.72     13948287.95        3085097.     13948514.65
#Sta/Elev= 30
  4618.2  122.12  4668.2  120.49  4748.2  115.92  4758.2  116.33  4768.2  115.99
  4778.2  114.85  4788.2  113.51  4808.2  109.61  4838.2  108.58  4858.2  109.02
  4868.2  109.93  4878.2  112.43  4888.2   114.2  4898.2  115.21  4973.3  115.13
  4973.6  114.58  4977.5  113.65  4983.3  110.09  4988.2  106.46    5001  104.47
  5007.7  106.14  5020.9  113.87  5027.5  115.93  5051.5  116.83  5141.5  117.64
  5191.5  118.98  5371.5  119.23  5401.5   117.6  5421.5  117.36  5467.4  120.42
#Mann= 6 ,-1 , 0
  4618.2     .09       0  4778.2    .026       0  4898.2     .07       0
  4973.3     .04       0  5027.5    .045       0  5051.5      .1       0
#XS Ineff= 2 , 0
       0 4978.18   114.4 5019.83       0   114.4
Permanent Ineff=
       F       F
#Block Obstruct= 2 , 0
       0    4950     115               0
Bank Sta=4973.3,5027.5
XS Rating Curve= 0
Exp/Cntr=.5,.3

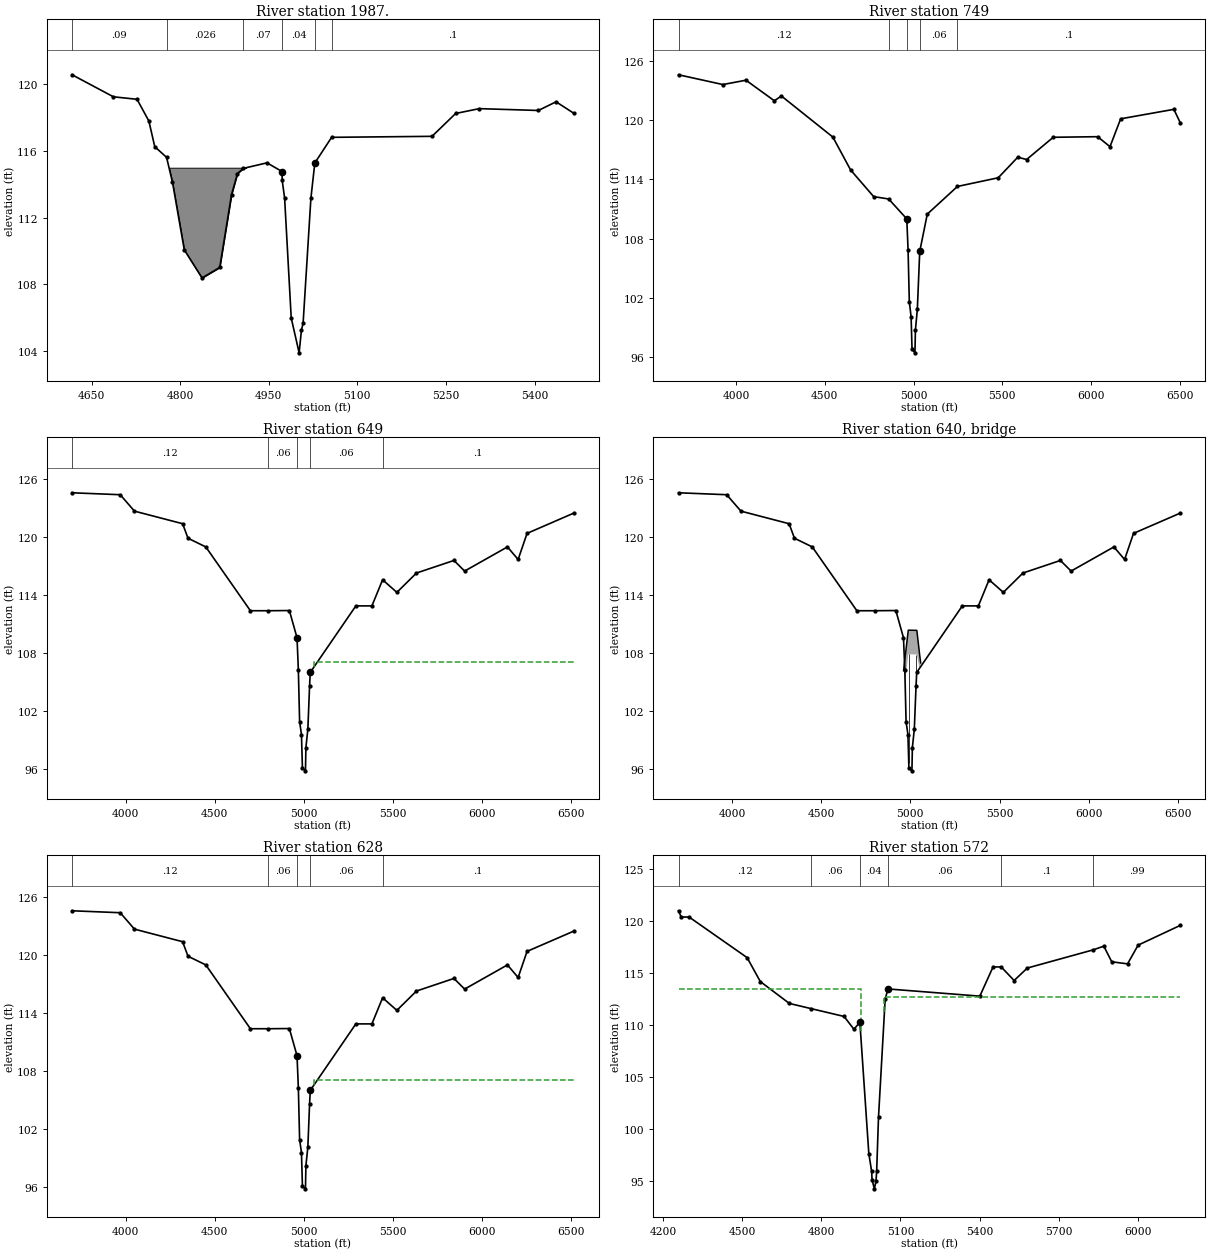
Type RM Length L Ch R = 1 ,1987.   ,1242.6,1238,1225
BEGIN DESCRIPTION:
S02_WOOD BRIDGE - XS 1
LIDAR overbanks, Interpolated channel
END DESCRIPTION:
XS GIS Cut Line= 4
      3085885.03     13948296.48        3085550.     13948201.36
      3085469.68     13948189.73      3085117.74     13948419.07
#Sta/Elev= 30
  4617.1  120.57  4687.1  119.25  4727.1   119.1  4747.1   117.8  4757.1  116.26
  4777.1  115.62  4787.1  114.12  4807.1  110.07  4837.1  108.39  4867.1  109.02
  4887.1  113.39  4897.1  114.65  4907.1  114.96  4947.1  115.29 4972.52  114.77
 4972.83  114.24 4976.92  113.18 4988.11  105.99 5001.51   103.9 5005.42  105.27
 5008.22  105.67 5021.43  113.17 5028.04  115.28  5056.5  116.82  5226.5  116.88
  5266.5  118.25  5306.5  118.54  5406.5  118.43  5436.5  118.95  5466.6  118.26
#Mann= 6 ,-1 , 0
  4617.1     .09       0  4777.1    .026       0  4907.1     .07       0
 4972.52     .04       0 5028.04    .045       0  5056.5      .1       0
#XS Ineff= 2 , 0
       0 4900.18   114.4               0
Permanent Ineff=
       F       F
#Block Obstruct= 2 , 0
       0    4950     115               0
Bank Sta=4972.52,5028.04
XS Rating Curve= 0
Exp/Cntr=.3,.1

Type RM Length L Ch R = 1 ,749     ,89.5,100,106.2
BEGIN DESCRIPTION:
PL S1A U/S OF LOUETTA - XS 4
LIDAR overbanks, Interpolated channel
END DESCRIPTION:
XS GIS Cut Line= 5
      3086583.58     13948094.47      3085926.11     13947024.12
      3085858.65     13947021.37      3085780.15     13947022.38
      3084744.17     13948002.84
#Sta/Elev= 30
  3675.5   124.6  3925.5  123.61  4055.5  124.05  4215.5  121.97  4255.5  122.45
  4545.5  118.29  4645.5  114.96  4775.5  112.26    4860 112.022 4962.23     110
 4962.73  109.75 4969.51  106.81 4976.41  101.63 4986.51  100.08 4991.75    96.8
 5008.25   96.44 5010.75   98.74 5021.64  100.83 5035.13  106.71  5077.7  110.49
  5247.7  113.29  5477.7  114.17  5587.7  116.25  5637.7  116.02  5787.7  118.27
  6037.7  118.33  6107.7  117.32  6167.7  120.14  6467.7   121.1  6504.1  119.73
#Mann= 5 ,-1 , 0
  3675.5     .12       0    4860     .06       0 4962.73     .04       0
 5035.13     .06       0  5247.7      .1       0
Bank Sta=4962.23,5035.13
XS Rating Curve= 0
Exp/Cntr=.5,.3

Type RM Length L Ch R = 1 ,649     ,20.4,21,21.6
BEGIN DESCRIPTION:
PL S1A U/S OF LOUETTA - XS 3
END DESCRIPTION:
XS GIS Cut Line= 4
      3086571.37      13947991.8      3085913.93      13946938.3
       3085799.8      13946902.8      3084748.46       13947905.
#Sta/Elev= 30
    3700   124.6    3970   124.4    4050   122.7    4320   121.4    4350   119.9
    4450     119    4700   112.4    4800   112.4  4918.6  112.42  4961.4  109.61
  4968.9  106.31    4976  100.93  4986.4   99.59  4991.8   96.11  5008.8   95.84
  5011.3   98.25  5022.2  100.15  5031.8  104.58  5035.7  106.02  5291.4   112.9
  5381.4   112.9  5441.4   115.6  5521.4   114.3  5631.4   116.3  5841.4   117.6
  5901.4   116.5  6141.4     119  6201.4   117.7  6251.4   120.4  6513.9   122.5
#Mann= 5 ,-1 , 0
    3700     .12       0    4800     .06       0  4961.4     .04       0
  5031.8     .06       0  5441.4      .1       0
#XS Ineff= 2 , 0
       0  4967.2     107    5057       0  107.14
Permanent Ineff=
       F       F
Bank Sta=4961.4,5035.7
XS Rating Curve= 0
Exp/Cntr=.5,.3

Type RM Length L Ch R = 3 ,640     ,,,
BEGIN DESCRIPTION:
PL S1A U/S OF LOUETTA
END DESCRIPTION:
Bridge Culvert--1,0,-1,-1, 0
Deck Dist Width WeirC Skew NumUp NumDn MinLoCord MaxHiCord MaxSubmerge Is_Ogee
9,2.5,2.6,0, 6, 6, , , .95, 0, 0,0,,
    4962  4970.5  4988.3  5036.4    5051    5058
   106.2  107.59  110.39  110.37  108.02     107
   103.7  105.09  107.89  107.87  105.52   104.5
    4962  4970.5  4988.3  5036.4    5051    5058
   106.2  107.59  110.39  110.37  108.02     107
   103.7  105.09  107.89  107.87  105.52   104.5
Pier Skew, UpSta & Num, DnSta & Num=  ,4991, 2 ,4991, 2 , 0 , 0 , 0 ,,
     1.5     1.5
      95   108.2
     1.5     1.5
      95   108.2
Pier Skew, UpSta & Num, DnSta & Num=  ,5031.5, 2 ,5031.5, 2 , 0 , 0 , 0 ,,
     1.5     1.5
      95   108.2
     1.5     1.5
      95   108.2
BR Coef=-1 , 1 , 1 ,1.25, 0 ,,,.8,0,2,0,
WSPro=,,,, 1 ,,,, 0 ,,,, 0 ,,,,-1 ,-1 ,-1 , 0 , 0 , 0 , 0 , 0
BC Design=,, 0 ,, 0 ,,,,,,
BC HTab HWMax=124.6

Type RM Length L Ch R = 1 ,628     ,44.7,56,67.2
BEGIN DESCRIPTION:
PL S1A U/S OF LOUETTA - XS 2
END DESCRIPTION:
XS GIS Cut Line= 4
      3086570.63      13947971.8      3085913.19      13946918.3
      3085799.06      13946882.8      3084747.72       13947885.
#Sta/Elev= 30
    3700   124.6    3970   124.4    4050   122.7    4320   121.4    4350   119.9
    4450     119    4700   112.4    4800   112.4  4918.6  112.42  4961.4  109.61
  4968.9  106.31    4976  100.93  4986.4   99.59  4991.8   96.11  5008.8   95.84
  5011.3   98.25  5022.2  100.15  5031.8  104.58  5035.7  106.02  5291.4   112.9
  5381.4   112.9  5441.4   115.6  5521.4   114.3  5631.4   116.3  5841.4   117.6
  5901.4   116.5  6141.4     119  6201.4   117.7  6251.4   120.4  6513.9   122.5
#Mann= 5 ,-1 , 0
    3700     .12       0    4800     .06       0  4961.4     .04       0
  5031.8     .06       0  5441.4      .1       0
#XS Ineff= 2 , 0
       0  4967.2     107    5057       0  107.14
Permanent Ineff=
       F       F
Bank Sta=4961.4,5035.7
XS Rating Curve= 0
Exp/Cntr=.5,.3

Type RM Length L Ch R = 1 ,572     ,100.8,98,95.3
BEGIN DESCRIPTION:
S1_LOUETTA-XS3
END DESCRIPTION:
XS GIS Cut Line= 4
 3086272.125124313947425.8602969      3085945.58     13946889.56
      3085773.88     13946821.32 3084994.3474897 13947582.306829
#Sta/Elev= 30
    4259  120.97    4269  120.37    4299  120.37    4519  116.47    4569  114.17
    4679  112.07    4760  111.58  4886.4  110.82  4923.9  109.59  4946.4  110.26
  4980.3   97.65    4991   95.93  4992.6   95.15  5001.2   94.26  5007.5   94.99
    5010   95.93    5017  101.14  5042.3  112.51  5053.3  113.46  5401.1  112.77
  5451.1  115.57    5482  115.58  5531.1  114.27  5581.1  115.47    5830  117.21
  5871.1  117.57  5901.1  116.07  5961.1  115.87  6001.1  117.67  6161.1  119.57
#Mann= 6 ,-1 , 0
    4259     .12       0    4760     .06       0  4946.4     .04       0
  5053.3     .06       0    5482      .1       0    5830     .99       0
#XS Ineff= 2 , 0
       0  4948.8   113.5 5039.59       0  112.65
Permanent Ineff=
       F       F
Bank Sta=4946.4,5053.3
XS Rating Curve= 0
Exp/Cntr=.5,.3

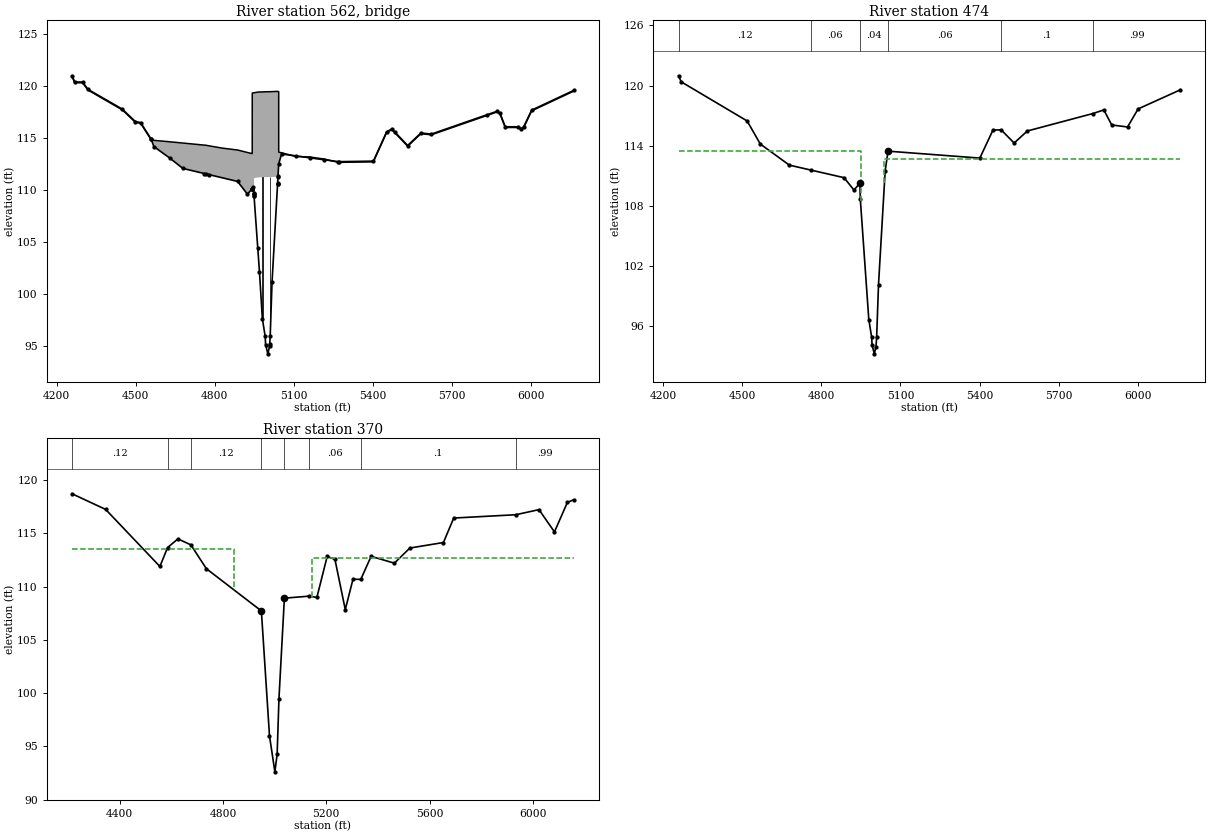
Type RM Length L Ch R = 3 ,562     ,,,
BEGIN DESCRIPTION:
LOUETTA ROAD; Width measured from Arcview VRR
Structure ID: K124-02-00-S1
END DESCRIPTION:
Bridge Culvert--1,0,-1,-1, 0
Deck Dist Width WeirC Skew NumUp NumDn MinLoCord MaxHiCord MaxSubmerge Is_Ogee
10,75,2.6,0, 68, 68, , , .95, 0, ,,,
    4259    4269    4299    4319    4449    4499    4519  4558.6    4559    4569
    4629    4679    4760  4765.6    4779  4782.9  4831.7  4886.4  4923.9  4939.9
 4941.89    4942 4942.11  4946.4 4947.99  4948.1 4948.21 4948.81 4948.88    4963
  4969.4  4980.3    4991  4992.6  5001.2  5007.5  5008.1    5010    5017 5037.89
    5038 5038.11 5039.55 5039.62  5042.3 5042.33  5053.3  5106.5    5160  5215.2
  5265.3  5269.1  5401.1  5451.1  5471.1    5482  5531.1  5581.1  5621.1    5830
  5871.1  5881.1  5901.1  5951.1  5961.1  5971.1  6001.1  6161.1
   120.9   120.3   120.3   119.6   117.7   116.5   116.4  114.83   114.8  114.77
  114.63  114.51  114.31   114.3  114.24  114.22  114.01  113.84   113.6   113.5
  113.51  119.31  119.31  119.33  119.34  119.34  119.34  119.34  119.34   119.4
  119.41  119.42  119.43  119.43  119.44  119.44  119.44  119.44  119.45  119.47
  119.47  119.47  119.46  119.46  119.44  113.64  113.57  113.22  113.17  112.97
  112.67  112.65   112.7   115.5   115.8  115.51   114.2   115.4   115.3  117.14
   117.5   117.3     116     116   115.8     116   117.6   119.5
                                                                                
                                                                                
                                                                  111.14   111.2
  111.21  111.22  111.23  111.23  111.24  111.24  111.24  111.24  111.25  111.27
  111.27  111.27  111.26
                                                                                
                                                                
    4259    4269    4299    4319    4449    4499    4519  4558.6    4559    4569
    4629    4679    4760  4765.6    4779  4782.9  4831.7  4886.4  4923.9  4939.9
 4941.89    4942 4942.11  4946.4 4947.99  4948.1 4948.21 4948.81 4948.88    4963
  4969.4  4980.3    4991  4992.6  5001.2  5007.5  5008.1    5010    5017 5037.89
    5038 5038.11 5039.55 5039.62  5042.3 5042.33  5053.3  5106.5    5160  5215.2
  5265.3  5269.1  5401.1  5451.1  5471.1    5482  5531.1  5581.1  5621.1    5830
  5871.1  5881.1  5901.1  5951.1  5961.1  5971.1  6001.1  6161.1
   120.9   120.3   120.3   119.6   117.7   116.5   116.4  114.83   114.8  114.77
  114.63  114.51  114.31   114.3  114.24  114.22  114.01  113.84   113.6   113.5
  113.51  119.31  119.31  119.33  119.34  119.34  119.34  119.34  119.34   119.4
  119.41  119.42  119.43  119.43  119.44  119.44  119.44  119.44  119.45  119.47
  119.47  119.47  119.46  119.46  119.44  113.64  113.57  113.22  113.17  112.97
  112.67  112.65   112.7   115.5   115.8  115.51   114.2   115.4   115.3  117.14
   117.5   117.3     116     116   115.8     116   117.6   119.5
                                                                                
                                                                                
                                                                  111.14   111.2
  111.21  111.22  111.23  111.23  111.24  111.24  111.24  111.24  111.25  111.27
  111.27  111.27  111.26
                                                                                
                                                                
Pier Skew, UpSta & Num, DnSta & Num=  ,4980.3, 2 ,4980.3, 2 , 0 , 0 , 0 ,,
     1.3     1.3
   96.48  112.22
     1.3     1.3
   95.54  111.28
Pier Skew, UpSta & Num, DnSta & Num=  ,5010, 2 ,5010, 2 , 0 , 0 , 0 ,,
     1.3     1.3
    94.6  112.24
     1.3     1.3
   93.66   111.3
BR Coef= 1 , 1 , 1 ,1.25, 0 ,,,.8,0,2,0,
WSPro=,,,, 1 ,,,, 0 ,,,, 0 ,,,,-1 ,-1 ,-1 , 0 , 0 , 0 , 0 , 0
BR U #Sta/Elev= 65
    4259  120.97    4269  120.37    4299  120.37    4319  119.67    4449  117.77
    4499  116.57    4519  116.47  4558.6  114.89    4559  114.87    4569  114.17
    4629  113.07    4679  112.07    4760  111.58  4765.6  111.55    4779  111.47
  4886.4  110.82  4923.9  109.59  4939.9  110.07 4941.89  110.13    4942  110.13
 4942.11  110.13  4946.4  110.26 4947.99   109.7  4948.1  109.66 4948.21  109.62
 4948.81  109.41  4948.9  109.38    4963  104.39  4969.4  102.12  4980.3   97.65
    4991   95.93  4992.6   95.15  5001.2   94.26  5007.5   94.99  5008.1   95.17
    5010   95.93    5017  101.14 5037.89  110.53    5038  110.58 5038.11  110.63
  5039.5  111.26 5039.62  111.31  5042.3  112.51  5053.3  113.46  5106.5  113.28
    5160  113.09  5215.2   112.9  5265.3  112.73  5269.1  112.72  5401.1  112.77
  5451.1  115.57  5471.1  115.87    5482  115.58  5531.1  114.27  5581.1  115.47
  5621.1  115.37    5830  117.21  5871.1  117.57  5881.1  117.37  5901.1  116.07
  5951.1  116.07  5961.1  115.87  5971.1  116.07  6001.1  117.67  6161.1  119.57
BR U #Mann= 6
    4259     .12    4760     .06  4946.4     .04  5053.3     .06    5482      .1
    5830     .99
BR D #Sta/Elev= 65
    4259  120.97    4269  120.37    4299  120.37    4319  119.67    4449  117.77
    4499  116.57    4519  116.47  4558.6  114.89    4559  114.87    4569  114.17
    4629  113.07    4679  112.07    4760  111.58  4765.6  111.55    4779  111.47
  4886.4  110.82  4923.9  109.59  4939.9  110.07 4941.89  110.13    4942  110.13
 4942.11  110.13  4946.4  110.26 4947.99  108.71  4948.1  108.67 4948.21  108.63
 4948.81  108.42  4948.9  108.39    4963   103.4  4969.4  101.13  4980.3   96.66
    4991   94.94  4992.6   94.16  5001.2   93.27  5007.5      94  5008.1   94.18
    5010   94.94    5017  100.15 5037.89  109.54    5038  109.59 5038.11  109.64
 5039.51  110.27 5039.62  110.32  5042.3  111.52  5053.3  113.46  5106.5  113.28
    5160  113.09  5215.2   112.9  5265.3  112.73  5269.1  112.72  5401.1  112.77
  5451.1  115.57  5471.1  115.87    5482  115.58  5531.1  114.27  5581.1  115.47
  5621.1  115.37    5830  117.21  5871.1  117.57  5881.1  117.37  5901.1  116.07
  5951.1  116.07  5961.1  115.87  5971.1  116.07  6001.1  117.67  6161.1  119.57
BR D #Mann= 6
    4259     .12    4760     .06  4946.4     .04  5053.3     .06    5482      .1
    5830     .99
BC Design=,, 0 ,, 0 ,,,,,,
BC HTab HWMax=120.97

Type RM Length L Ch R = 1 ,474     ,122.7,104,86.6
BEGIN DESCRIPTION:
S1_LOUETTA-XS2
END DESCRIPTION:
XS GIS Cut Line= 4
 3086291.836097713947341.1397043      3085961.81     13946799.12
      3085771.83     13946723.61 3084983.005734813947493.6152752
#Sta/Elev= 30
    4259  120.97    4269  120.37    4519  116.47    4569  114.17    4679  112.07
    4760  111.58  4886.4  110.82  4923.9  109.59  4946.4  110.26 4947.99  108.71
  4980.3   96.66    4991   94.94  4992.6   94.16  5001.2   93.27  5007.5      94
    5010   94.94    5017  100.15  5042.3  111.52  5053.3  113.46  5401.1  112.77
  5451.1  115.57    5482  115.58  5531.1  114.27  5581.1  115.47    5830  117.21
  5871.1  117.57  5901.1  116.07  5961.1  115.87  6001.1  117.67  6161.1  119.57
#Mann= 6 ,-1 , 0
    4259     .12       0    4760     .06       0  4946.4     .04       0
  5053.3     .06       0    5482      .1       0    5830     .99       0
#XS Ineff= 2 , 0
       0  4948.8   113.5 5039.59       0  112.65
Permanent Ineff=
       F       F
Bank Sta=4946.4,5053.3
XS Rating Curve= 0
Exp/Cntr=.5,.3

Type RM Length L Ch R = 1 ,370     ,0,0,0
BEGIN DESCRIPTION:
S1_LOUETTA-XS1
LIDAR overbanks, Interpolated channel
END DESCRIPTION:
XS GIS Cut Line= 4
      3086287.32     13947237.27      3085926.11     13946647.06
      3085740.18     13946645.32      3084978.49     13947389.75
#Sta/Elev= 30
  4215.9  118.73  4345.9  117.26  4555.9   111.9  4585.9  113.68  4625.9  114.49
  4675.9  113.93  4735.9  111.69  4948.9  107.72  4980.3   95.99  5001.2    92.6
    5010   94.27    5017   99.48    5038  108.92  5133.8  109.11  5163.8  108.99
  5203.8  112.85  5233.8  112.56  5273.8  107.85  5303.8  110.71  5333.8  110.68
  5373.8  112.85  5463.8  112.21  5523.8  113.63  5653.8  114.15  5693.8  116.45
  5933.8  116.76  6023.8  117.24  6083.8  115.15  6133.8  117.92  6158.9  118.17
#Mann= 8 ,-1 , 0
  4215.9     .12       0  4585.9     .06       0  4675.9     .12       0
  4948.9     .04       0    5038     .12       0  5133.8     .06       0
  5333.8      .1       0  5933.8     .99       0
#XS Ineff= 2 , 0
       0  4844.8   113.5 5143.59       0  112.65
Permanent Ineff=
       F       F
Bank Sta=4948.9,5038
XS Rating Curve= 0
Exp/Cntr=.3,.1

Chan Stop Cuts=-1